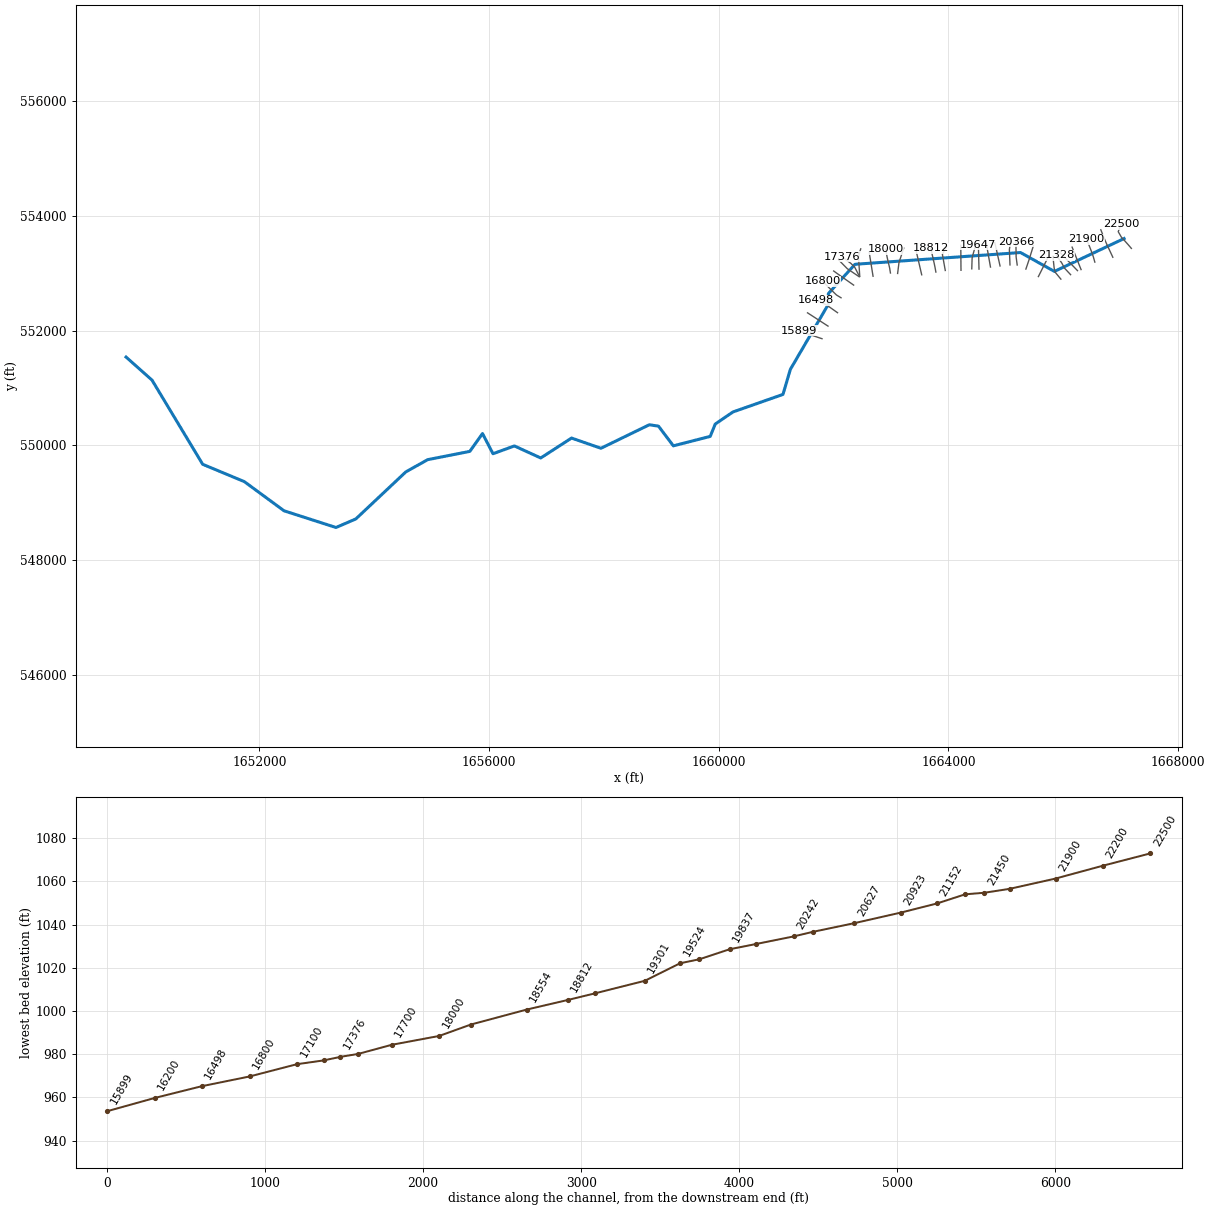
--- GrandstaffRn.prj (project) ---

Proj Title=GrandstaffRn
Current Plan=p01
Default Exp/Contr=0,0
English Units
Geom File=g01
Flow File=f01
Plan File=p01
BEGIN DESCRIPTION:
---------- MODELED AS PART OF WVEM CTP PROGRAM, 2025----------
Stream Name: Grandstaff Run
Flood Zone: AFH
Marshall County, WV
HEC-RAS Version: RAS 6.6
Vertical Datum: NAVD88
Projection: NAD 1983 StatePlane West Virginia N FIPS 4701 (US Feet)
Terrain: 1-meter West Virginia FEMA R3 South Central (collected 2018-2019)
Land Use: 2024 NLCD
Hydrologic Method:
Duda et al., "Estimation of magnitude and frequency of floods for rural, unregulated streams in and near Virginia and West Virginia." September 8, 2025.
Additional Model Notes:
Large dam near river station 1700. Modeled as structure with framing XS.
END DESCRIPTION:
DSS Export Rating Curves= 0
DSS Export Rating Curve Sorted= 0
DSS Export Volume Flow Curves= 0
DXF OffsetX= 0
DXF OffsetY= 0
DXF ScaleX= 0
DXF ScaleY= 0

--- GrandstaffRn.p01 (plan) ---

Plan Title=Floodplain
Program Version=6.60
Short Identifier=Floodplain
Geom File=g01
Flow File=f01
Subcritical Flow
K Sum by GR= 0
Std Step Tol= 0.01
Critical Tol= 0.01
Num of Std Step Trials= 20
Max Error Tol= 0.3
Flow Tol Ratio= 0.001
Split Flow NTrial= 30
Split Flow Tol= 0.02
Split Flow Ratio= 0.02
Log Output Level= 0
Friction Slope Method= 1
Unsteady Friction Slope Method= 2
Unsteady Bridges Friction Slope Method= 1
Parabolic Critical Depth
Global Vel Dist= 0 , 0 , 0
Global Log Level= 0
CheckData=False
Encroach Param=-1 ,0,0, 0
Flow Ratio Tolerance=0.1
Flow Ratio Min Ratio=0.5
Flow Ratio Max Ratio=4
Flow Ratio Max Iterations= 10
Mapping Interval=1HOUR
Computation Time Step Use Courant=        0
Computation Time Step Use Time Series=    0
Computation Time Step Count To Double=0
Computation Time Step Max Doubling=0
Computation Time Step Max Halving=0
Computation Time Step Residence Courant=0
Run HTab= 0
Run UNet= 0
Run Sediment= 0
Run PostProcess= 0
Run WQNet= 0
Run RASMapper=-1
UNET Theta= 0
UNET Theta Warmup= 0
UNET ZTol= 0
UNET ZSATol= 0
UNET MxIter= 0
UNET Max Iter WO Improvement= 0
UNET MaxInSteps= 0
UNET DtIC= 0
UNET DtMin= 0
UNET MaxCRTS= 0
UNET WFStab= 0
UNET SFStab= 0
UNET WFX= 1
UNET SFX= 1
UNET Gravity=32.17405
UNET 1D Methodology=Finite Difference
UNET DSS MLevel= 1
UNET Pardiso=0
UNET DZMax Abort= 0
UNET Use Existing IB Tables= 0
UNET Froude Reduction=False
UNET Froude Limit= 0
UNET Froude Power= 0
UNET D1 Cores= 0
UNET WindReference=Eulerian
UNET WindDragFormulation=Hsu (1988)
UNET D2 Coriolis=0
UNET D2 Cores= 0
UNET D2 Theta= 1
UNET D2 Theta Warmup= 1
UNET D2 Z Tol= 0.01
UNET D2 Volume Tol= 0.01
UNET D2 Max Iterations= 20
UNET D2 Advanced Convergence=0
UNET D2 WS Max Tol=0.15
UNET D2 WS RMS Tol=0.002
UNET D2 WS Stall Tol=1
UNET D2 Equation= 0
UNET D2 RampUpFraction=0.1
UNET D2 TimeSlices= 1
UNET D2 Turbulence Formulation=Non-Conservative (original)
UNET D2 Eddy Viscosity=0.3
UNET D2 Transverse Eddy Viscosity=0.1
UNET D2 Smagorinsky Mixing=0
UNET D2 BCVolumeCheck=0
UNET D2 Cores=0
UNET D2 SolverType=PARDISO (Direct)
UNET D2 Minimum Iterations= 3
UNET D2 Maximum Iterations= 30
UNET D2 Restart Number= 10
UNET D2 Relaxation Coeff=1.3
UNET D2 SOR Precondition Iterations= 10
UNET D2 ILUT Maximum Fill= 8
UNET D2 ILUT Tolerance=1E-08
UNET D2 Convergence Tolerance=0.00001
PS Theta= 1
PS WS Tol= 0.01
PS Volume Tol= 0.01
PS Max Iterations= 20
PS Equation= 0
PS Advance Time Step=-1
PS Target Courant=0.9
PS Time Slices= 1
PS Iterate With 2D=0
PS Project Initial WSE from DS=-1
PS Ramp Up Initial WSE from US=-1
PS Cores=0
UNET D1D2 MaxIter= 0
UNET D1D2 ZTol=0.01
UNET D1D2 QTol=0.1
UNET D1D2 MinQTol=1
Write IC File= 0
Write IC File at Fixed DateTime=0
Write IC File at Sim End=0
Echo Input=False
Echo Parameters=False
Echo Output=False
Write Detailed= 0
HDF Write Warmup=0
HDF Write Time Slices=0
HDF Flush=0
HDF Compression= 1
HDF Chunk Size= 1
HDF Spatial Parts= 1
HDF Use Max Rows=0
HDF Fixed Rows= 1
Calibration Method= 0
Calibration Iterations= 20
Calibration Max Change=0.05
Calibration Tolerance=0.2
Calibration Maximum=1.5
Calibration Minimum=0.5
Calibration Optimization Method= 1
WQ AD Non Conservative
WQ ULTIMATE=-1
WQ Max Comp Step=1HOUR
WQ Output Interval=15MIN
WQ Output Selected Increments= 0
WQ Create Restart=0
WQ Fixed Restart=0
WQ System Summary=0
WQ Write To DSS=0
Sorting and Armoring Iterations= 10
XS Update Threshold= 0.02
Bed Roughness Predictor= 0
Processes Affected by Predictor=Sediment Only
Hydraulics Update Threshold= 0.02
Energy Slope Method= 1
Volume Change Method= 1
Sediment Retention Method= 0
Sediment TS Multiplier= 1
Warm Up Method= 0
XS Weighting Method= 0
Number of US Weighted Cross Sections= 1
Number of DS Weighted Cross Sections= 1
Upstream XS Weight=0
Main XS Weight=1
Downstream XS Weight=0
Number of DS XS's Weighted with US Boundary= 1
Upstream Boundary Weight= 1
Weight of XSs Associated with US Boundary= 0
Number of US XS's Weighted with DS Boundary= 1
Downstream Boundary Weight= 0.5
Weight of XSs Associated with DS Boundary= 0.5
Percentile Method= 0
Sediment Output Level= 3
Mass or Volume Output= 0
Output Increment Type= 1
Profile and TS Output Increment= 1
Transport Output Increment 1
XS Output Flag= 0
XS Output Increment= 10
Read HDF5 Sediment Hotstart= 0
Sediment Hotstart Type= 0
Write Gradation File= 0
Read Gradation Hotstart= 0
Write HDF5 File= 1
Write Binary Output= 1
Write DSS Sediment File= 0
DSS Sediment Output Type= 1
SV Curve= 0
Specific Gage Flag= 0
Subcell Erosion Methods= 0
Subcell Deposition Methods= 0
Advection Scheme= 1
Matrix Solver= 0
Implicit Weighting Factor= 1
Maximum Outer Loop Convergence Iterations= 5
Convergence Maximum Absolute= 0.001
Convergence RMSE= 0.0001
Grain Fractions Max Abs Error= 0.001
Max Subgrid Regions= 1
Max Subgrid Length Scale= 3.402823E+38
Initial Layer Thickness= 3
Min Layer Thickness= 0.1
Max Layer Thickness= 6
Number of Layers= 5

--- GrandstaffRn.f01 (steady flow) ---

Flow Title=Flow
Program Version=6.60
Number of Profiles= 1
Profile Names=P100yr
River Rch & RM=GrandstaffRn,Main            ,22500
     691
River Rch & RM=GrandstaffRn,Main            ,21900
     786
River Rch & RM=GrandstaffRn,Main            ,18812
     923
River Rch & RM=GrandstaffRn,Main            ,17487
    1050
River Rch & RM=GrandstaffRn,Main            ,15530
    1260
River Rch & RM=GrandstaffRn,Main            ,11970
    1440
River Rch & RM=GrandstaffRn,Main            ,10087
    1600
River Rch & RM=GrandstaffRn,Main            ,6600
    1790
Boundary for River Rch & Prof#=GrandstaffRn,Main            , 1
Up Type= 0
Dn Type= 3
Dn Slope=0.07
DSS Import GetInterval= 0
DSS Import GetPeak= 0
DSS Import FillOption= 0

--- GrandstaffRn.g01 (geometry) ---

Geom Title=Geometry
Program Version=6.60

River Reach=GrandstaffRn    ,Main
Reach XY= 30
      1667059.46      553602.683     1665845.826      553030.095
     1665255.435      553358.826      1662373.63      553154.044
     1661909.346      552643.649     1661909.973      552458.054
     1661247.284      551322.388     1661118.757      550886.585
     1660248.572       550581.49     1659940.129      550371.262
     1659851.655      550155.352     1659209.866      549990.806
     1658950.863      550334.176     1658791.231      550358.007
     1657949.088      549948.542      1657436.92      550126.326
     1656900.271      549779.371     1656441.632      549989.188
     1656069.072      549853.344     1655886.155      550205.057
     1655665.578      549894.367     1654931.284      549749.752
      1654551.16      549537.103     1653680.876        548717.5
     1653334.615      548568.232      1652430.14      548859.184
     1651738.931       549367.08     1651013.252       549669.32
     1650130.803      551136.287     1649678.937      551537.522

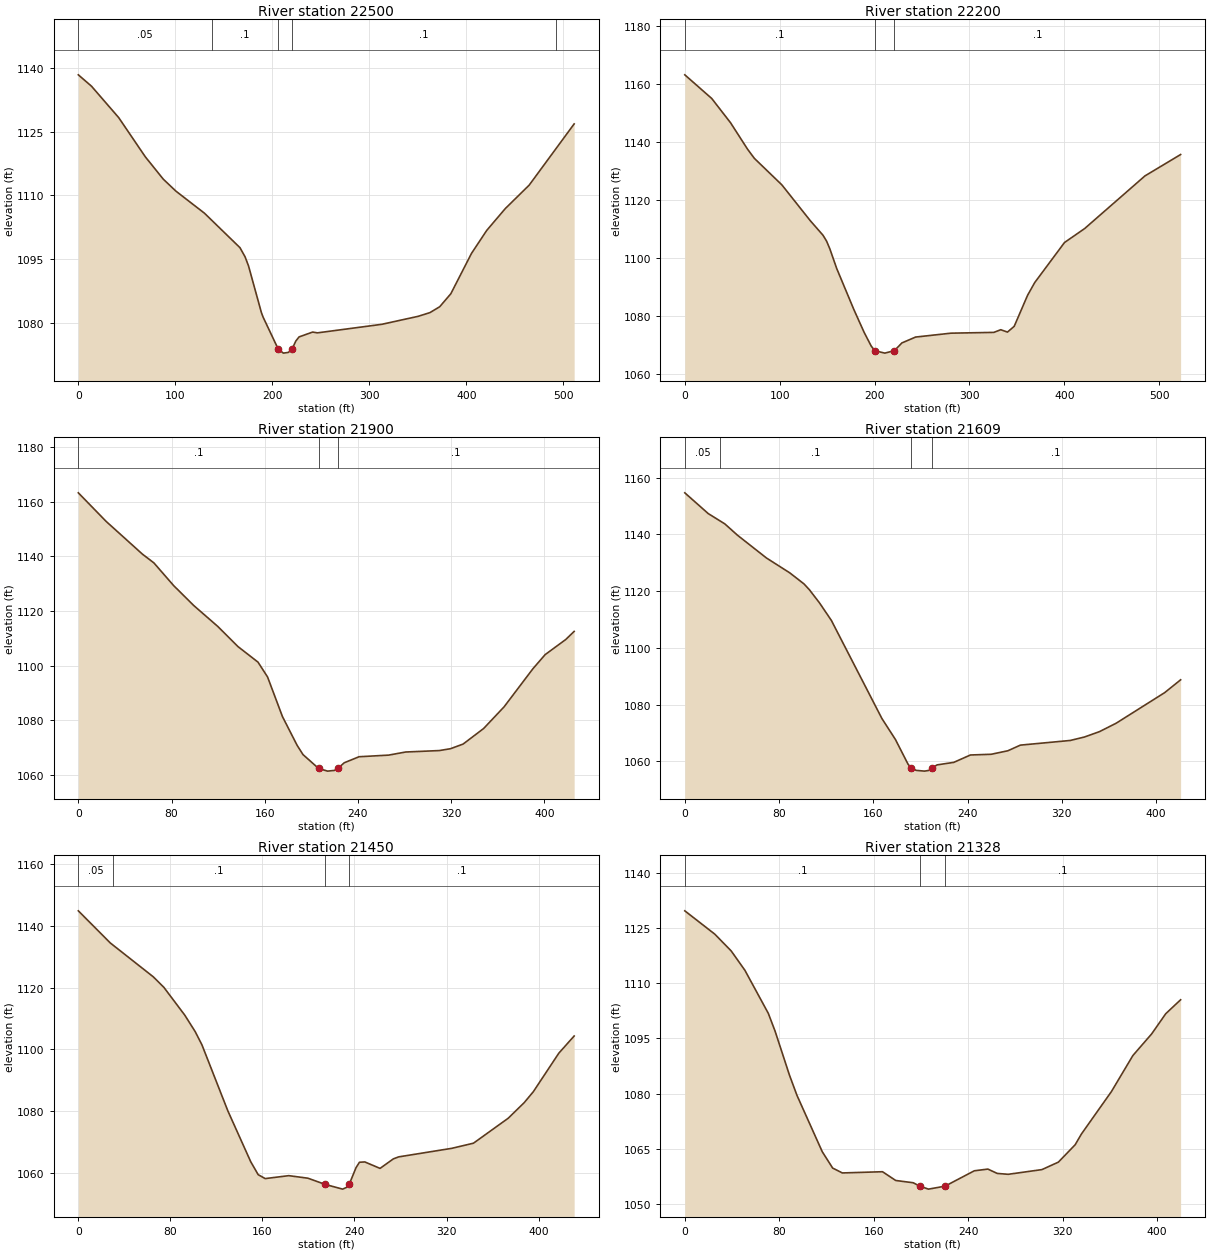
Type RM Length L Ch R = 1 ,22500   ,301.5,300,297.5
XS GIS Cut Line= 6
1667186.34725368553430.8202730861667129.33227584553497.244680926
1667079.32318951553553.1425350011667011.98277301553627.069552511
1666957.15219199553722.2345277241667005.52645923553852.196756073
#Sta/Elev= 30
       0 1138.34    13.6 1135.66    41.6 1128.29      69 1119.09    87.5 1113.84
   100.5 1111.03     130 1105.83   166.6 1097.73   171.8  1095.6   175.4 1093.45
   188.7 1082.46   190.4 1081.43  205.991073.916   211.3 1072.96   216.5 1073.13
  220.251073.917   224.2 1075.82   227.5 1076.77   241.5 1077.91   246.4 1077.72
   312.8 1079.73   350.3 1081.61   362.4 1082.48   372.4 1083.85   383.9 1086.91
   405.2 1096.39   420.9 1101.79     440 1106.91   464.7 1112.44     511 1126.81
#Mann= 5 ,-1,0
       0     .05       0  137.54      .1       0  205.99    .045       0
  220.25      .1       0  492.37     .06       0
Bank Sta=205.99,220.25
XS Rating Curve= 0 ,0
Exp/Cntr(USF)=0,0
Exp/Cntr=0.3,0.1

Type RM Length L Ch R = 1 ,22200   ,301.4,300,299.5
XS GIS Cut Line= 6
1666863.26915967553276.3159889281666826.45000759553355.692470595
1666794.89101559553423.7294080111666752.81170343553514.445105836
1666722.84457175553583.2205588371666654.09799237553755.073298608
#Sta/Elev= 30
       0 1163.21    28.4 1155.05    48.2  1146.7    66.1  1137.6    73.3 1134.42
   102.3 1125.28   132.2 1112.95   145.7  1107.9   149.5 1105.84   152.9  1103.2
   160.1 1096.46   178.2 1082.29     189 1074.44   196.4 1069.76  200.151068.122
   210.8 1067.27   220.91068.123   228.9  1070.8   243.3 1072.81   280.6 1074.15
   325.8 1074.42     333 1075.34   340.1 1074.53   347.2 1076.51   361.3 1087.21
   368.8 1091.58   400.2  1105.4   421.4  1110.2     485 1128.36   522.6 1135.73
#Mann= 3 ,-1,0
       0      .1       0  200.15    .045       0   220.9      .1       0
Bank Sta=200.15,220.9
XS Rating Curve= 0 ,0
Exp/Cntr(USF)=0,0
Exp/Cntr=0.3,0.1

Type RM Length L Ch R = 1 ,21900   ,291.4,290.8,291.4
XS GIS Cut Line= 6
1666549.85738492553191.9345960021666525.93256401553276.532852009
1666502.65997276553347.9638115021666466.22008501553441.088297173
1666438.89008717553510.9313333331666407.00498034553592.415094256
#Sta/Elev= 30
       0 1163.24    23.9 1152.76      55 1140.79    64.8  1137.6    81.8 1129.27
      99 1121.99   119.7  1114.3     137 1106.93   154.2 1101.23   162.4  1095.8
   175.2 1081.27   187.7 1070.82   192.8 1067.38  206.251062.284   213.9 1061.32
   219.8 1061.58  222.631062.286   228.2 1064.38   240.9 1066.59   266.2 1067.18
   280.9 1068.32   309.8 1068.85   319.4 1069.53   330.2 1071.23   347.8 1076.92
   365.4 1084.88   390.1 1098.81   400.6 1103.98   418.3 1109.53   425.5 1112.49
#Mann= 3 ,-1,0
       0      .1       0  206.25    .045       0  222.63      .1       0
Bank Sta=206.25,222.63
XS Rating Curve= 0 ,0
Exp/Cntr(USF)=0,0
Exp/Cntr=0.3,0.1

Type RM Length L Ch R = 1 ,21609   ,152.2,159.5,161.2
XS GIS Cut Line= 2
1666310.17788998 553061.917329751666154.40509184553452.810058504
#Sta/Elev= 30
       0 1154.69    19.9 1147.37      34 1143.73    44.6 1139.78    69.3 1131.71
    89.1 1126.47   101.1 1122.59   105.7 1120.54   114.3 1115.89   124.4 1109.69
   167.3 1075.09   178.8 1067.68   189.4 1059.05  192.261057.551   196.5 1056.81
   203.5 1056.55   207.1  1056.8  209.66 1057.55   214.1 1058.75   228.3 1059.64
   242.4 1062.24     260 1062.49   274.2 1063.73   284.8 1065.72   327.1 1067.36
   339.1 1068.57   351.9 1070.47     366 1073.42   407.3 1084.24   420.8 1088.75
#Mann= 4 ,-1,0
       0     .05       0      30      .1       0  192.26    .045       0
  209.66      .1       0
Bank Sta=192.26,209.66
XS Rating Curve= 0 ,0
Exp/Cntr(USF)=0,0
Exp/Cntr=0.3,0.1

Type RM Length L Ch R = 1 ,21450   ,123.5,121.8,117.4
XS GIS Cut Line= 2
1666248.16662967553043.4206557791665948.77509862553353.333933919
#Sta/Elev= 30
       0 1144.84    27.8 1134.43    65.1 1123.49    74.3 1120.09    92.5 1111.08
   101.6 1105.71   107.4 1101.48   129.9 1080.12   149.8 1063.64   156.3 1059.43
   162.4 1058.16   182.9 1059.11   199.5 1058.29  214.791056.249   229.7 1054.75
   233.9 1055.45  235.361056.251   241.3 1061.67   244.3 1063.45     249 1063.55
   262.2 1061.46   273.8 1064.55   278.4 1065.19   324.6 1067.96   343.4 1069.62
   373.6  1077.7   387.5 1082.75   395.4 1086.28   417.6 1098.77   430.9 1104.32
#Mann= 4 ,-1,0
       0     .05       0      30      .1       0  214.79    .045       0
  235.36      .1       0
Bank Sta=214.79,235.36
XS Rating Curve= 0 ,0
Exp/Cntr(USF)=0,0
Exp/Cntr=0.3,0.1

Type RM Length L Ch R = 1 ,21328   ,178.3,176.2,174.6
XS GIS Cut Line= 4
 1666128.2320701 552972.912640421666019.84525702553089.300245915
1665977.33314753553171.1360566711665882.79047759553310.641379595
#Sta/Elev= 30
       0 1129.68    25.4 1123.34    39.3 1118.77    50.9 1113.51    70.7 1101.81
    76.5 1096.92    88.6 1085.03      95 1079.49   116.4 1064.18   125.2 1059.74
   133.4 1058.42   167.4 1058.75   178.6 1056.37   193.4 1055.75     199 1054.82
   206.3 1054.02  220.31 1054.82   245.1    1059   256.6 1059.47   264.5 1058.29
   273.8 1058.05   302.4 1059.33   316.3 1061.36   330.5 1066.08   335.8    1069
   361.2 1080.54   379.4 1090.35   395.3 1096.23   407.2 1101.71   419.8  1105.5
#Mann= 3 ,-1,0
       0      .1       0     199    .045       0  220.31      .1       0
Bank Sta=199,220.31
XS Rating Curve= 0 ,0
Exp/Cntr(USF)=0,0
Exp/Cntr=0.3,0.1

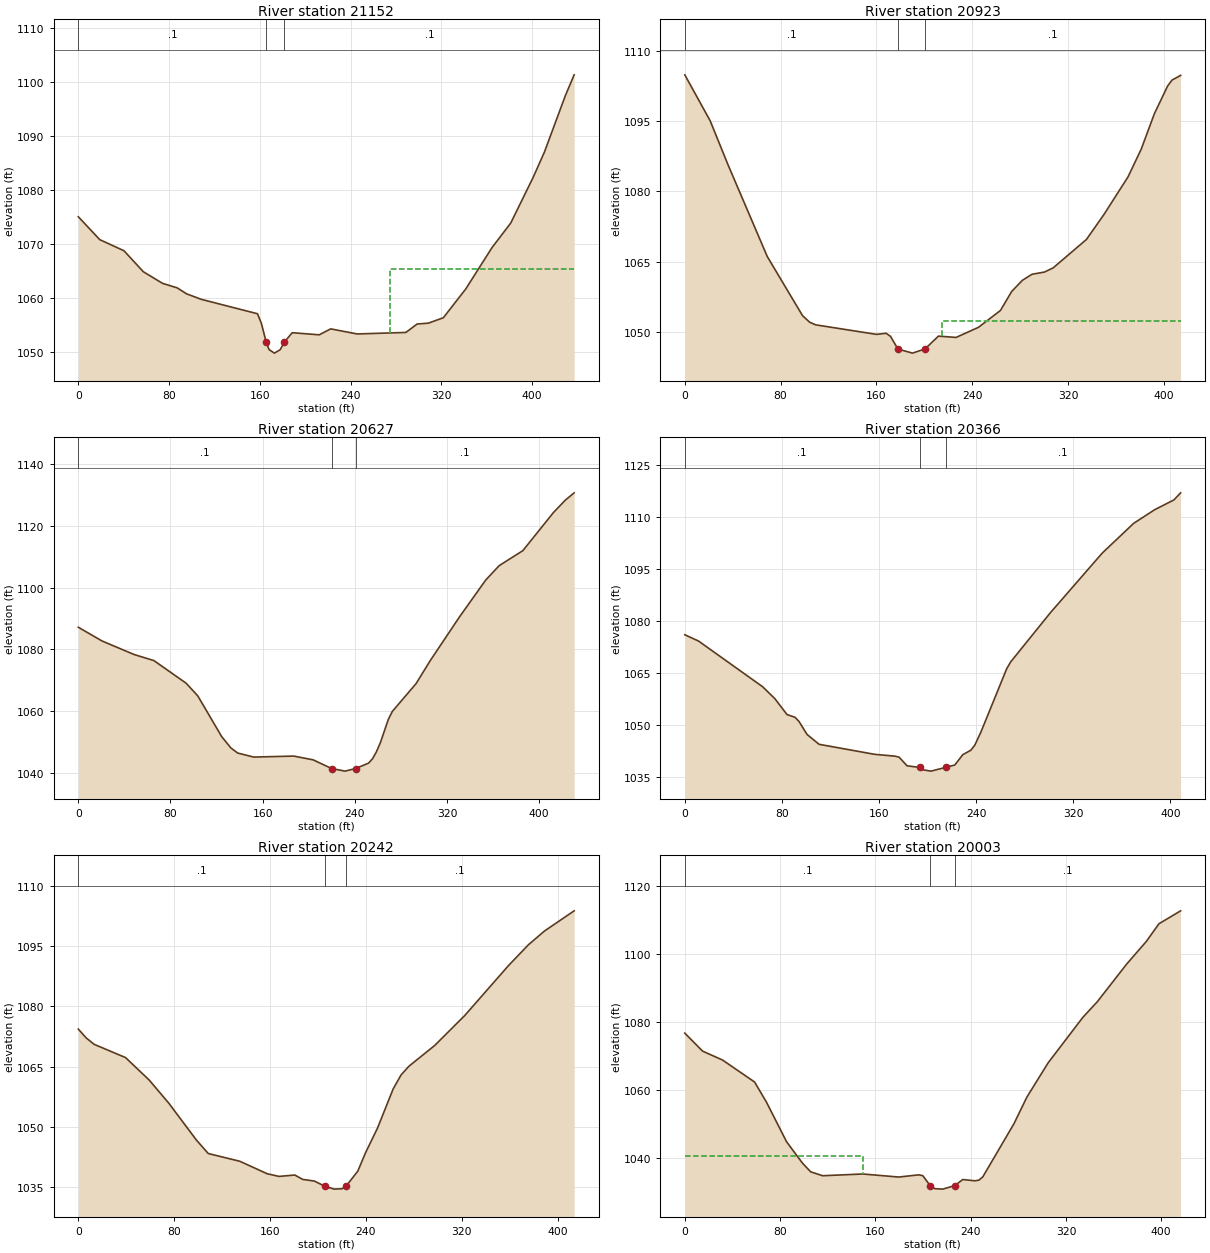
Type RM Length L Ch R = 1 ,21152   ,232.9,228.3,218.9
XS GIS Cut Line= 4
1665958.85735892552895.2283731211665862.19723625553011.864921146
1665841.57641008553088.5486184661665819.66678227553293.468078532
#Sta/Elev= 30
       0 1075.07    18.9 1070.83    40.2 1068.78    57.3 1064.89    74.3 1062.73
    87.1 1061.91    95.5 1060.79   108.4 1059.78   157.9 1057.11   161.3 1055.36
  165.61 1051.84   168.1 1050.48   172.8 1049.82   177.9 1050.45   181.7 1051.89
   188.5  1053.6   212.3 1053.21   222.4 1054.31   245.8 1053.37   288.7 1053.65
   298.6 1055.21   308.5 1055.37   321.7 1056.37   341.5 1061.71   364.6 1069.36
   381.1  1073.9   400.9 1082.38   410.8 1087.05   429.3 1097.53     437 1101.35
#Mann= 3 ,0,0
       0      .1       0  165.61    .045       0   181.7      .1       0
#XS Ineff= 2 , 0
                          275.01         1065.32
Permanent Ineff=
       F       F
Bank Sta=165.61,181.7
XS Rating Curve= 0 ,0
Exp/Cntr(USF)=0,0
Exp/Cntr=0.3,0.1

Type RM Length L Ch R = 1 ,20923   ,293.5,296,296.5
XS GIS Cut Line= 2
1665566.88582094552940.0617673151665752.87629994553309.917119825
#Sta/Elev= 30
       0 1104.83    21.2 1095.04    35.9  1085.8    68.9 1066.14    98.3 1053.58
   104.3 1052.17   109.3 1051.62   160.1 1049.59   168.1 1049.83   171.8 1049.16
  177.961046.474   190.1  1045.6  200.491046.474   211.8 1049.22   226.5 1048.94
   245.2 1051.09   263.6 1054.69   272.9 1058.71   281.9  1061.1     290 1062.39
   300.3 1062.85   307.6 1063.75   335.4  1069.8     350 1075.11   370.1 1083.12
   381.1 1089.01   392.1 1096.56   403.1 1102.43   406.8 1103.71     414 1104.71
#Mann= 3 ,-1,0
       0      .1       0  177.96    .045       0  200.49      .1       0
#XS Ineff= 2 , 0
                          215.16         1052.51
Permanent Ineff=
       F       F
Bank Sta=177.96,200.49
XS Rating Curve= 0 ,0
Exp/Cntr(USF)=0,0
Exp/Cntr=0.3,0.1

Type RM Length L Ch R = 1 ,20627   ,258.4,261.8,264.3
XS GIS Cut Line= 3
  1665349.424865553070.7549753771665403.26151083553230.119692725
1665481.18624332553480.507219439
#Sta/Elev= 30
       0 1087.16    20.6 1082.72    48.3 1078.37    65.6 1076.39    93.6 1069.08
   103.7 1064.99   124.4 1051.86   132.4 1048.18   138.3 1046.53   152.2 1045.22
     187 1045.54   203.8 1044.33  219.881041.522   231.5 1040.68  240.691041.522
   251.9 1043.26   255.4 1044.69   258.8 1046.95   262.2 1049.88   269.1  1057.4
   272.5 1059.93   293.2 1068.97   305.7 1076.51   330.9 1090.52   353.6  1102.4
   365.3 1107.06   385.9 1111.92   412.3 1124.17   422.8 1128.25   430.4 1130.59
#Mann= 3 ,-1,0
       0      .1       0  219.88    .045       0  240.69      .1       0
Bank Sta=219.88,240.69
XS Rating Curve= 0 ,0
Exp/Cntr(USF)=0,0
Exp/Cntr=0.3,0.1

Type RM Length L Ch R = 1 ,20366   ,121.2,123.1,121.4
XS GIS Cut Line= 3
1665197.90629661553141.3177674981665179.34149458553282.157630804
1665175.25770786553548.437476964
#Sta/Elev= 30
       0 1075.97    11.3 1074.16    64.1 1060.99    74.2 1057.55    84.2 1052.97
    90.8 1052.19    94.1 1050.96   100.7 1047.24   110.6  1044.4   156.4 1041.51
   173.2 1040.98   176.5  1040.7   183.1  1038.2  193.481037.737   196.2 1037.05
   202.8 1036.67   214.81037.737   222.4 1038.43     229 1041.42   235.6 1042.69
   238.9 1044.17   243.9 1047.93   265.1 1066.14   268.4 1068.14   301.2 1082.35
   343.8 1099.49   369.7 1108.07   387.1 1112.02   402.9 1114.83   408.4 1116.87
#Mann= 3 ,-1,0
       0      .1       0  193.48    .045       0   214.8      .1       0
Bank Sta=193.48,214.8
XS Rating Curve= 0 ,0
Exp/Cntr(USF)=0,0
Exp/Cntr=0.3,0.1

Type RM Length L Ch R = 1 ,20242   ,235.4,239.7,240.7
XS GIS Cut Line= 3
1665072.34460518553142.6813363831665061.73829908553410.718035656
1665083.86934452553554.448727647
#Sta/Elev= 30
       0 1074.31     6.6 1072.11    13.2 1070.53    39.4 1067.23    59.1 1061.66
    75.6 1055.85    98.5 1046.74   108.4 1043.38   134.7 1041.46   157.6 1038.35
   167.5 1037.69   180.6 1038.04   187.2 1036.95     197 1036.53  205.461035.283
   213.5 1034.53     220 1034.62  223.461035.282   233.2 1039.02   239.7 1043.61
   249.6 1049.69   262.7 1059.45   269.3 1062.93   275.9  1065.1   297.4 1070.26
   322.4 1077.69   358.9  1090.1   375.5 1095.27   388.8 1098.67   413.7 1103.72
#Mann= 3 ,-1,0
       0      .1       0  205.46    .045       0  223.46      .1       0
Bank Sta=205.46,223.46
XS Rating Curve= 0 ,0
Exp/Cntr(USF)=0,0
Exp/Cntr=0.3,0.1

Type RM Length L Ch R = 1 ,20003   ,166.4,165.3,164.3
XS GIS Cut Line= 2
1664899.24782525553124.9058586661664808.49005347553531.215455474
#Sta/Elev= 30
       0 1076.86    14.9 1071.57    31.7 1068.94    58.6 1062.48    68.6 1056.54
    85.5 1044.89    98.9 1038.59   105.7 1036.08   115.7 1034.93   149.4 1035.44
   179.6 1034.54   196.4 1035.19   199.8 1034.95  205.991032.049   209.9 1031.13
   216.6 1030.99  226.751032.047   233.4 1033.81   243.5 1033.44   246.9 1033.62
   250.2 1034.59   276.4 1050.24   287.2 1058.03     305 1068.09   334.3 1081.53
   346.3 1086.07   371.2 1097.24   387.5 1103.81   398.1 1109.01   416.3 1112.81
#Mann= 3 ,-1,0
       0      .1       0  205.99    .045       0  226.75      .1       0
#XS Ineff= 2 , 0
          149.82 1040.67
Permanent Ineff=
       F       F
Bank Sta=205.99,226.75
XS Rating Curve= 0 ,0
Exp/Cntr(USF)=0,0
Exp/Cntr=0.3,0.1

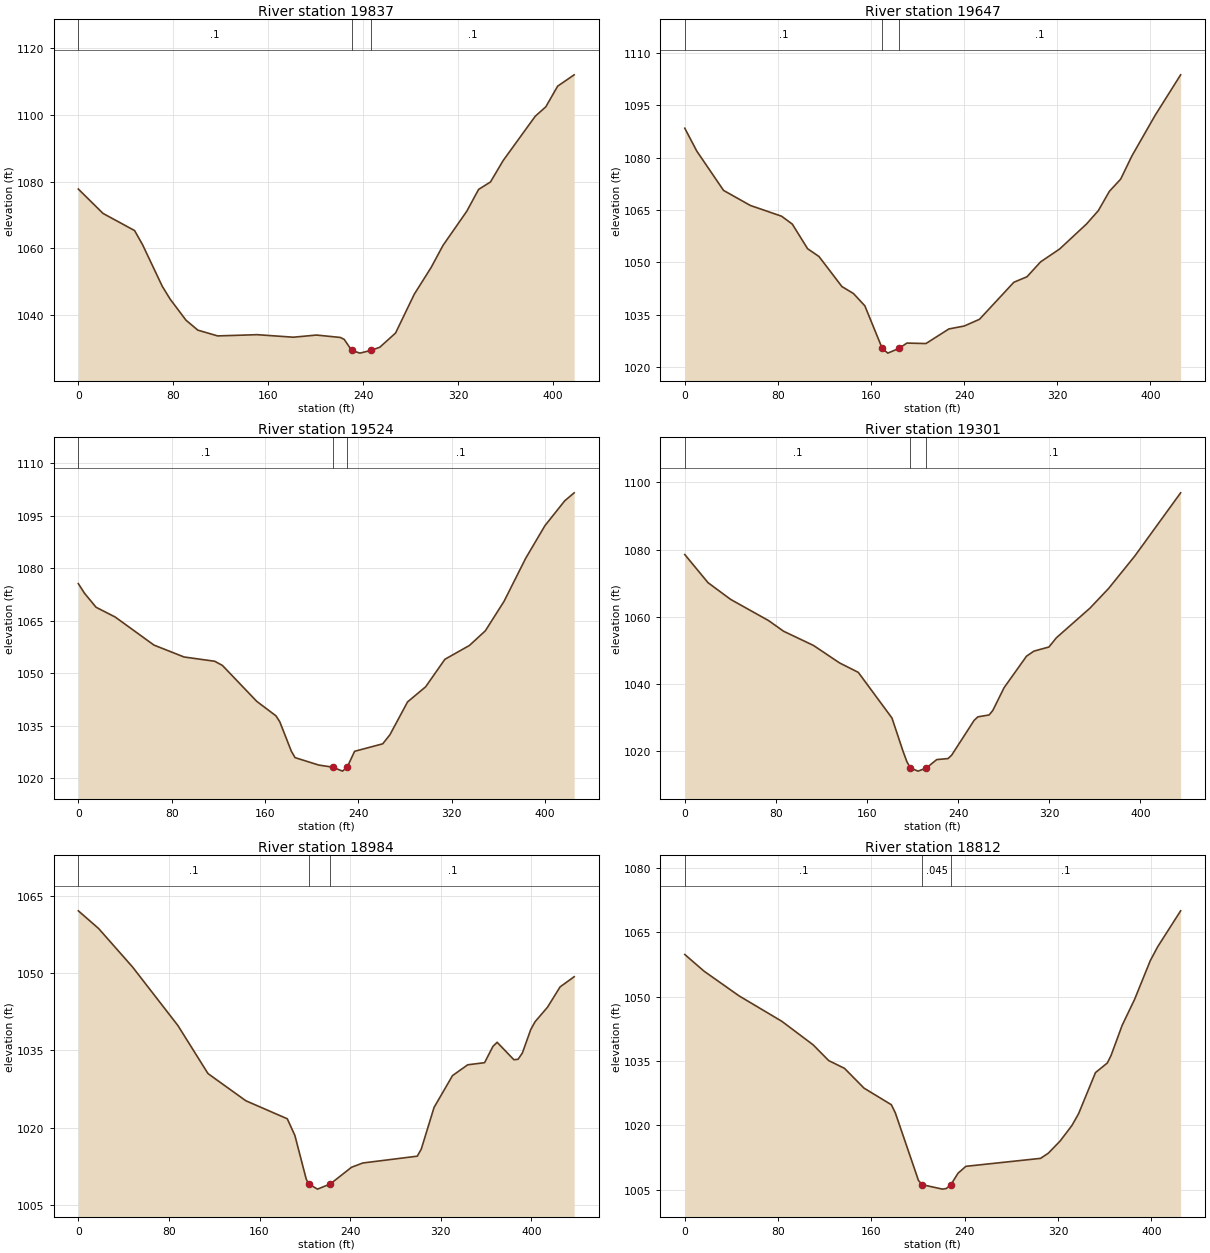
Type RM Length L Ch R = 1 ,19837   ,190,190.2,188.3
XS GIS Cut Line= 2
1664732.61740961 553105.887259011664659.78778925553517.297135742
#Sta/Elev= 30
       0 1077.77    20.8 1070.47    47.4 1065.33    54.1 1061.11    70.7 1048.65
    77.4 1044.76    90.7 1038.47   100.7 1035.48   117.4 1033.75   150.7 1034.12
   181.2 1033.36   200.7 1034.01   220.7 1033.29     224 1032.73  230.351029.418
   237.3 1028.59   246.61029.418     254 1030.35   267.3 1034.61   283.1 1046.26
   297.3 1054.28   307.3 1060.89   327.3 1071.11   337.3 1077.67   347.3  1079.9
     358 1086.33     385 1099.59   393.9 1102.41   403.9 1108.62   417.8 1112.01
#Mann= 3 ,-1,0
       0      .1       0  230.35    .045       0   246.6      .1       0
Bank Sta=230.35,246.6
XS Rating Curve= 0 ,0
Exp/Cntr(USF)=0,0
Exp/Cntr=0.3,0.1

Type RM Length L Ch R = 1 ,19647   ,122.6,123.1,118.2
XS GIS Cut Line= 2
1664532.63706596553070.0715918661664521.90076613 553495.97346076
#Sta/Elev= 30
       0 1088.44    10.3 1081.89    33.3 1070.62    56.3 1066.31    83.2 1063.22
    92.4 1060.95   105.5 1053.91   115.3 1051.67     135 1043.06   144.9 1041.07
   154.7 1037.54  169.591025.371   174.4 1023.98  184.26 1025.37   190.8 1026.86
   207.2 1026.73   226.9 1030.91   240.1 1031.75   253.2 1033.68   282.7 1044.29
     294 1045.87   305.7 1050.14   322.1 1053.84   345.1 1060.98   355.3 1064.82
   364.8 1070.36   374.5 1073.86   384.1 1080.48   404.1 1092.14     426 1103.75
#Mann= 3 ,-1,0
       0      .1       0  169.59    .045       0  184.26      .1       0
Bank Sta=169.59,184.26
XS Rating Curve= 0 ,0
Exp/Cntr(USF)=0,0
Exp/Cntr=0.3,0.1

Type RM Length L Ch R = 1 ,19524   ,217.6,223,221.5
XS GIS Cut Line= 4
1664406.89855428553075.0896269951664412.73499609553262.859883955
1664425.97681569553315.7644048831664474.67658821553491.799020783
#Sta/Elev= 30
       0  1075.6     5.3 1072.85    15.2 1068.86    31.6 1066.07    64.8 1058.07
    90.6 1054.67   116.9 1053.45   123.5 1052.26     153 1041.99   169.4 1037.88
   172.7 1036.17   182.6 1027.77   185.8 1025.95   206.1 1023.83  217.981023.237
   226.4  1022.1  230.491023.236   236.8 1027.76   260.9 1029.89   267.1 1032.49
   282.2 1041.85   297.7 1046.16   314.2 1054.01   335.2 1057.95   348.9 1062.15
   364.9 1070.55   383.5 1082.86   399.9 1092.11   416.9 1099.23     425 1101.51
#Mann= 3 ,-1,0
       0      .1       0  217.98    .045       0  230.49      .1       0
Bank Sta=217.98,230.49
XS Rating Curve= 0 ,0
Exp/Cntr(USF)=0,0
Exp/Cntr=0.3,0.1

Type RM Length L Ch R = 1 ,19301   ,314.3,316.7,317.9
XS GIS Cut Line= 2
1664219.03386517553049.4588348541664215.65499031553484.698297963
#Sta/Elev= 30
       0 1078.51    20.4 1070.13    40.3 1065.14    73.6 1058.83    86.7 1055.67
     113 1051.43   135.9 1046.22   152.3 1043.42   181.9 1029.81   191.7 1019.81
     195 1016.79  198.041014.929   204.8 1013.99  212.081014.927   221.2 1017.43
   231.1 1017.73   234.3 1018.75     254 1029.11   257.3 1030.16   267.2 1030.73
   270.4 1032.06   280.3 1038.84     300 1048.23   306.5 1049.74   319.7 1050.97
   326.2 1053.71   355.7 1062.54   372.1 1068.42   395.1 1078.09   435.3  1096.9
#Mann= 3 ,-1,0
       0      .1       0  198.04    .045       0  212.08      .1       0
Bank Sta=198.04,212.08
XS Rating Curve= 0 ,0
Exp/Cntr(USF)=0,0
Exp/Cntr=0.3,0.1

Type RM Length L Ch R = 1 ,18984   ,170.9,172.2,172.2
XS GIS Cut Line= 3
1663945.40025388553046.4021667261663895.14655013553326.810853708
1663966.51767353553462.025703455
#Sta/Elev= 30
       0 1062.04    17.9 1058.62    47.9 1051.16    87.9 1039.84   114.5 1030.53
   147.9 1025.27   184.5 1021.78   191.2 1018.56   201.2 1010.13  203.251009.176
   211.2 1008.16  222.571009.176   241.2 1012.39   251.2 1013.22   299.3 1014.54
   302.8 1015.91   314.1 1023.98   330.4 1030.14   343.8 1032.23   358.7 1032.64
   366.1  1035.8   369.8 1036.59   384.6 1033.21   388.3  1033.3   392.1 1034.53
   399.5 1039.07   403.2 1040.54   414.3 1043.39   425.4 1047.32   437.8 1049.28
#Mann= 3 ,-1,0
       0      .1       0  203.25    .045       0  222.57      .1       0
Bank Sta=203.25,222.57
XS Rating Curve= 0 ,0
Exp/Cntr(USF)=0,0
Exp/Cntr=0.3,0.1

Type RM Length L Ch R = 1 ,18812   ,257.5,257.7,257.6
XS GIS Cut Line= 6
 1663781.8788862553018.2147593191663765.98685762553104.327776073
1663750.63190145553177.7502014031663728.52564646553275.275924979
1663711.94398671553348.4198075671663692.67040321553433.771014823
#Sta/Elev= 30
       0 1059.84    16.5 1055.95    46.5 1050.19    83.2 1044.25     110 1038.77
   123.4 1035.08   136.9 1033.28   153.6 1028.67   177.1 1024.78   180.5 1022.89
   200.4 1007.07  203.731006.117   220.9 1005.09   224.2 1005.23  228.071006.117
   234.3 1008.81     241 1010.41     305 1012.27   311.7 1013.48   321.8 1016.32
   331.9 1019.94   337.6 1022.68   352.1 1032.28   362.2 1034.51   365.5 1036.31
     375 1043.33   385.7 1049.41   399.1 1058.41   405.4 1061.63   425.1 1070.03
#Mann= 3 ,-1,0
       0      .1       0  203.73    .045       0  228.07      .1       0
Bank Sta=203.73,228.07
XS Rating Curve= 0 ,0
Exp/Cntr(USF)=0,0
Exp/Cntr=0.3,0.1

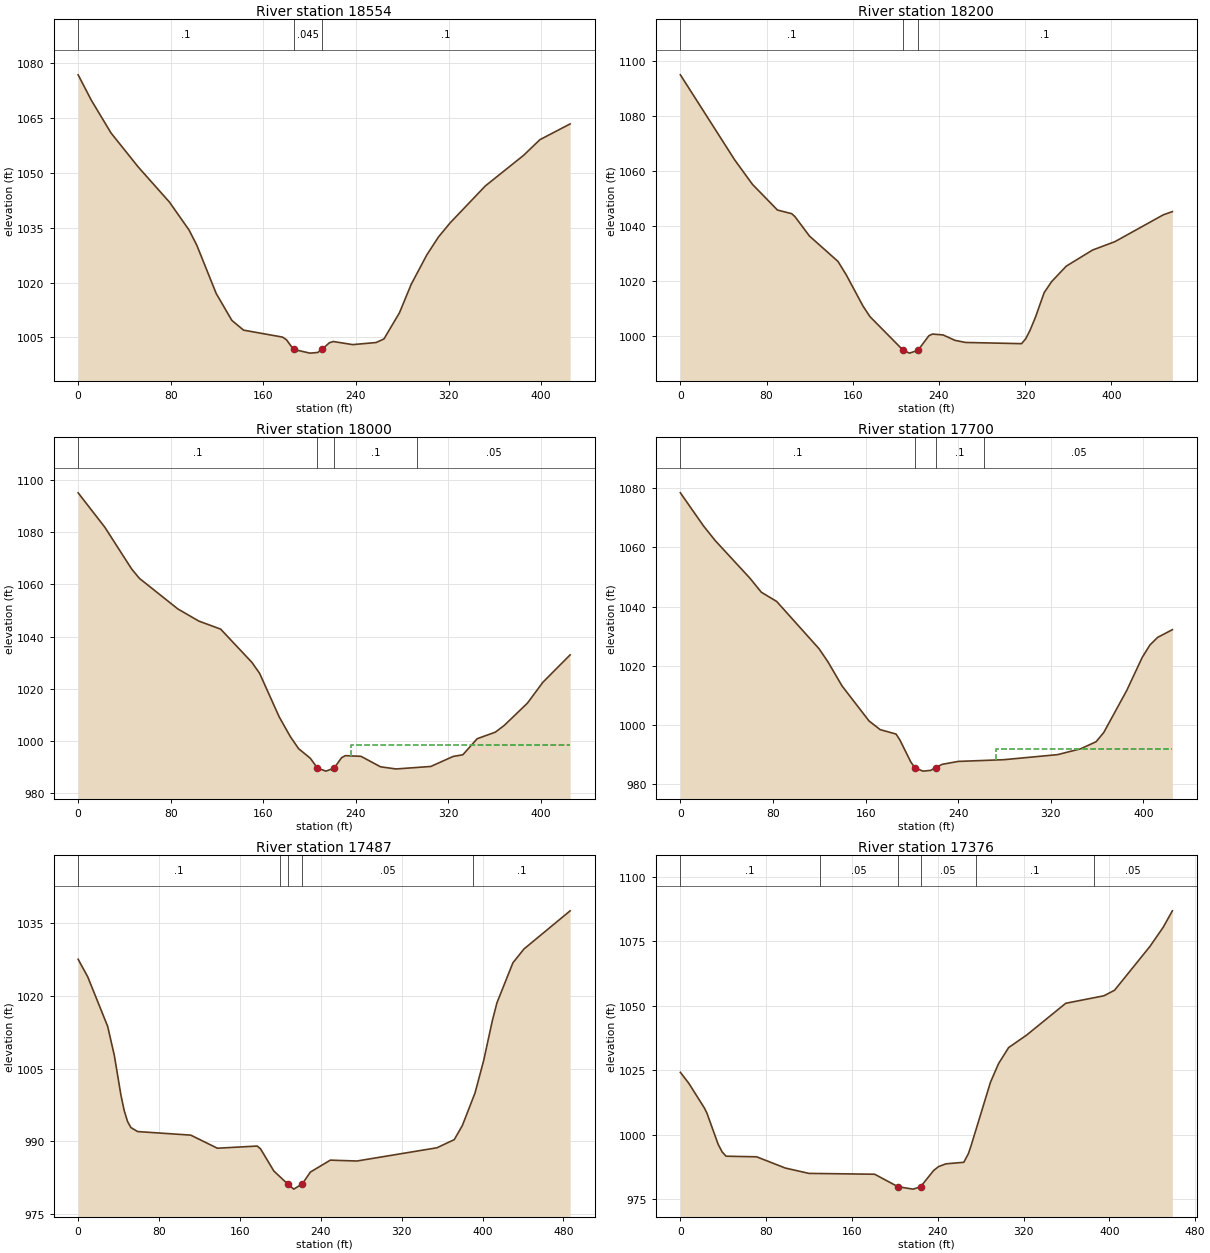
Type RM Length L Ch R = 1 ,18554   ,360.5,354.3,348.9
XS GIS Cut Line= 6
1663535.01469883552970.7253927591663515.19452849553055.950944096
 1663498.2060454553129.0013229251663475.55451591553226.402046755
1663458.56570475553299.452753678 1663438.7455344   553384.678305
#Sta/Elev= 30
       0 1076.82    11.4 1069.87    28.4 1060.92      52 1051.58    78.9    1042
    95.8 1034.37   102.5 1030.22   119.3 1016.98   132.8 1009.64   142.9 1006.98
   176.6 1005.07     180 1004.33  186.041001.721   200.2 1000.69   206.9 1000.86
  210.681001.723     217 1003.52   220.4 1003.87   237.2 1003.02   257.4 1003.59
   264.2 1004.57   277.6 1011.75   287.7  1019.5   301.2 1027.56   311.3 1032.48
   321.4 1036.34   351.7 1046.41   384.8  1054.8   398.9 1059.08     425 1063.39
#Mann= 3 ,-1,0
       0      .1       0  186.04    .045       0  210.68      .1       0
Bank Sta=186.04,210.68
XS Rating Curve= 0 ,0
Exp/Cntr(USF)=0,0
Exp/Cntr=0.3,0.1

Type RM Length L Ch R = 1 ,18200   ,197.2,200.1,204.7
XS GIS Cut Line= 3
1663115.63978707 552994.271686191663138.87919542553182.603038535
 1663222.3087587553436.146296986
#Sta/Elev= 30
       0 1095.13    50.4 1064.15    66.9 1055.23    90.1 1045.87   103.3 1044.55
   106.3  1043.5   119.8 1036.41   146.3 1027.15     154 1022.24   169.4 1010.98
     176 1007.03  206.89994.7513   212.7  993.74  220.52994.7487   230.7 1000.09
   234.1 1000.69   243.9 1000.36   254.8  998.41   264.7  997.63   316.7  997.19
   320.5  998.94   324.5 1001.97   329.7 1006.92   337.7 1015.79   344.6 1019.78
   358.2 1025.43   382.6 1031.29   403.4 1034.36   448.3 1044.13   456.7  1045.3
#Mann= 3 ,-1,0
       0      .1       0  206.89    .045       0  220.52      .1       0
Bank Sta=206.89,220.52
XS Rating Curve= 0 ,0
Exp/Cntr(USF)=0,0
Exp/Cntr=0.3,0.1

Type RM Length L Ch R = 1 ,18000   ,300.5,300,299.4
XS GIS Cut Line= 6
1662990.50164276553001.8421284261662976.58467583553088.383950084
1662959.51974934553161.4166124171662936.83475535553258.809790343
  1662922.219299553332.4152861681662906.00935768 553418.48532401
#Sta/Elev= 30
       0 1095.03    23.1 1081.84    46.3 1065.84      53 1062.27    86.2 1050.57
   104.3 1045.93   123.2 1042.84   150.2 1030.12   156.9  1025.9   173.8 1009.25
   183.5 1001.64   190.6  997.06   200.7   993.4  206.87989.6473   214.2  988.47
  221.29  989.63   227.7   993.6     231   994.4   244.5  994.14   261.4  990.13
   274.8   989.3   304.9  990.26   324.2   994.1   332.5  994.72     345 1000.89
   360.6 1003.38   368.4 1005.99   388.4 1014.51   401.7 1022.47   425.3 1032.99
#Mann= 4 ,-1,0
       0      .1       0  206.87    .045       0  221.29      .1       0
  292.65     .05       0
#XS Ineff= 2 , 0
                           236.1           998.6
Permanent Ineff=
       F       F
Bank Sta=206.87,221.29
XS Rating Curve= 0 ,0
Exp/Cntr(USF)=0,0
Exp/Cntr=0.3,0.1

Type RM Length L Ch R = 1 ,17700   ,214.3,213.1,212.2
XS GIS Cut Line= 6
1662687.63971567552945.7277393341662673.70732884553032.111424834
 1662661.7654236553106.1545838421662645.84321134553204.878795832
1662633.90163417 553278.92195484 1662619.9722001553365.306296512
#Sta/Elev= 30
       0 1078.42    20.1 1067.17    30.1 1062.28      60 1049.61    69.9 1044.84
    83.2 1041.71   119.8 1025.73   127.4 1021.36   139.7 1013.14     163 1001.32
   172.6   998.4   186.3  996.91   189.6  994.93   198.9  987.59  202.56985.5362
   209.5  984.38   216.2  984.63  220.41985.5351   226.1  986.67     240  987.66
   279.3  988.24   325.8  989.95   345.8  991.93   359.1  994.31   365.7  997.41
   385.6 1011.65   398.9 1022.77   405.6 1026.99   412.2 1029.55     425 1032.18
#Mann= 4 ,-1,0
       0      .1       0  202.56    .045       0  220.41      .1       0
   262.5     .05       0
#XS Ineff= 2 , 0
                          272.56          991.87
Permanent Ineff=
       F       F
Bank Sta=202.56,220.41
XS Rating Curve= 0 ,0
Exp/Cntr(USF)=0,0
Exp/Cntr=0.3,0.1

Type RM Length L Ch R = 1 ,17487   ,101.1,111.2,115.1
XS GIS Cut Line= 3
1662455.99057268552943.0043195931662433.65462227553292.614349017
1662472.83873035553423.098800326
#Sta/Elev= 30
       0 1027.57     9.5 1023.94    29.2 1013.73    35.8 1007.71    42.3  999.57
    45.6  996.31    48.9  994.09    52.2  992.84    58.8  992.02   111.4  991.28
   137.7  988.58   177.1  989.03   180.4  988.45   193.6  983.87   207.1 981.228
   213.3  980.14  221.72981.2267   229.7  983.66   249.4  986.12   275.7  985.94
   354.8  988.67     372  990.35     380  993.26   392.5  999.96   401.1 1006.68
   409.6 1014.84   414.2 1018.57     430 1026.83   440.9 1029.68   486.6 1037.56
#Mann= 5 ,-1,0
       0      .1       0     200     .05       0   207.1    .045       0
  221.72     .05       0  390.32      .1       0
Bank Sta=207.1,221.72
XS Rating Curve= 0 ,0
Exp/Cntr(USF)=0,0
Exp/Cntr=0.3,0.1

Type RM Length L Ch R = 1 ,17376   ,101.4,104.1,105.1
XS GIS Cut Line= 4
1662448.80610427552947.4248393641662366.96720041 553105.30303973
1662304.46032108 553167.165518241662151.09292644553284.446467083
#Sta/Elev= 30
       0 1024.15     7.8 1019.93    22.4  1010.3    24.8 1008.26    35.2  996.24
    38.9  993.28    42.6  991.59    71.1  991.36    97.8     987   119.8  984.92
   181.2  984.59     203  979.73     217  978.81  223.94  979.69   236.1  986.01
   240.8  987.57   247.7  988.63   264.3  989.23   268.6  992.59     271  995.54
   289.2 1020.33   296.7 1027.52   306.1 1033.76   322.8 1038.58   359.4 1050.96
     395 1053.86   404.9 1056.02   437.9 1073.03   450.3 1080.49   458.8 1086.84
#Mann= 6 ,-1,0
       0      .1       0     130     .05       0     203    .045       0
  223.94     .05       0  275.77      .1       0  385.77     .05       0
Bank Sta=203,223.94
XS Rating Curve= 0 ,0
Exp/Cntr(USF)=0,0
Exp/Cntr=0.3,0.1

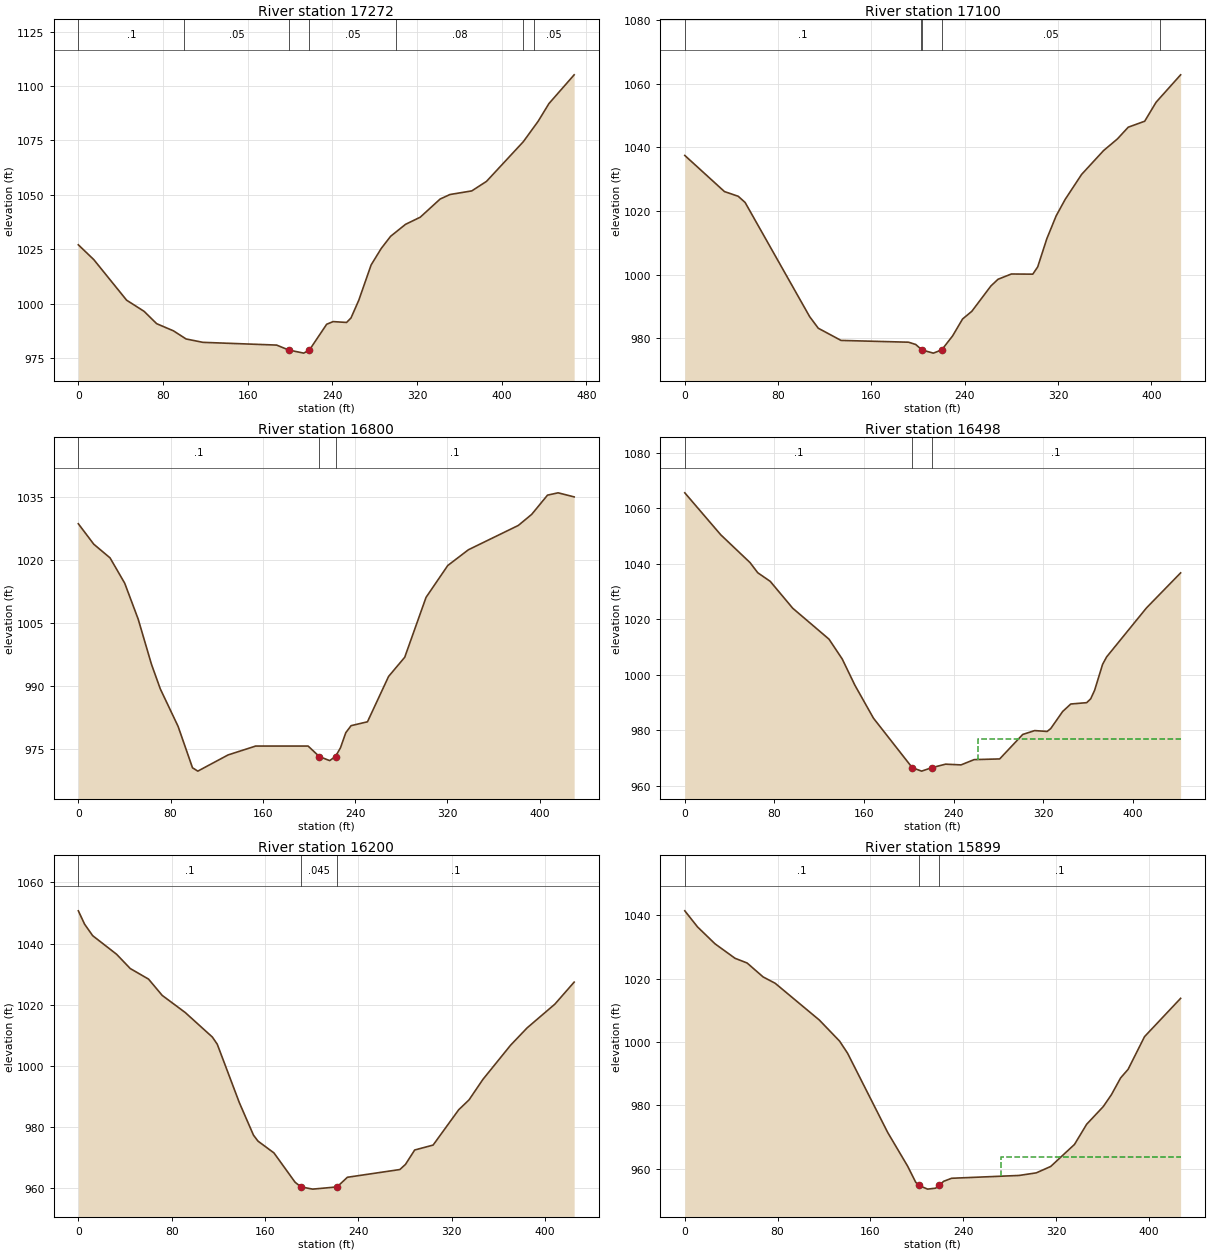
Type RM Length L Ch R = 1 ,17272   ,171.5,171.5,171.3
XS GIS Cut Line= 3
1662445.51077725552937.2013048131662238.51931617553077.850493435
1662085.43746113553233.216311557
#Sta/Elev= 30
       0    1027    14.6 1020.19    45.6 1001.53    62.1  996.41      74  990.72
    89.9  987.42   101.8  983.69   117.7  982.14   187.3  980.88  198.84978.6036
   212.9  977.18  218.29978.6053   234.6  990.46   240.7  991.68   253.4  991.29
   257.6  993.36     265 1001.58   276.6 1017.74   286.1 1025.28     295  1030.9
   309.1 1036.41     323 1039.69   341.8 1048.05   351.1 1050.13   371.7 1051.79
   385.6 1056.17   420.4 1074.43   434.4 1083.82   444.6 1091.96   468.4 1105.17
#Mann= 7 ,-1,0
       0      .1       0     100     .05       0  198.84    .045       0
  218.29     .05       0  300.26     .08       0  420.26      .1       0
  430.26     .05       0
Bank Sta=198.84,218.29
XS Rating Curve= 0 ,0
Exp/Cntr(USF)=0,0
Exp/Cntr=0.3,0.1

Type RM Length L Ch R = 1 ,17100   ,300.9,299.5,298.1
XS GIS Cut Line= 6
1662349.44222935552791.510528088 1662277.8508371552841.816857919
1662216.48809892552884.9355380831662134.66805258552942.428861424
1662073.30104934552985.5504943431662002.48623034553036.966402009
#Sta/Elev= 30
       0 1037.46      34 1026.12    45.8 1024.64    51.7  1022.7     107  986.87
   114.4  983.22   133.9  979.39   191.8  978.83     198   978.1  203.27 976.399
     213   975.4  220.17976.3985   229.5  980.78   238.1  986.12     246  988.52
   262.4  996.49   268.5  998.59   279.9 1000.24   298.3 1000.19   302.5 1002.48
   310.3  1011.3   318.3 1018.49     326 1023.64   340.1 1031.49   358.9 1038.97
   370.8 1042.64   380.1 1046.33   394.2  1048.2     404 1054.18     425 1062.77
#Mann= 5 ,-1,0
       0      .1       0   202.5     .05       0  203.27    .045       0
  220.17     .05       0   407.5      .1       0
Bank Sta=203.27,220.17
XS Rating Curve= 0 ,0
Exp/Cntr(USF)=0,0
Exp/Cntr=0.3,0.1

Type RM Length L Ch R = 1 ,16800   ,300.2,302.4,301.8
XS GIS Cut Line= 6
1662129.96694651552570.6841980811662051.16986001552618.795650423
1661997.21491542552670.890362501 1661925.9066591  552741.0043955
1661873.45466426552794.6555349231661812.44559993 552857.44084242
#Sta/Elev= 30
       0 1028.59    13.4 1023.72    27.5 1020.47    40.2 1014.45    51.9 1005.89
    63.4  995.16    71.1  989.27    86.5  980.37      99  970.51   103.6  969.72
   129.8  973.57   153.8  975.69   199.2  975.69   208.9   973.2   217.9  972.22
  222.98   973.2   227.3  975.28   231.9  978.87   236.5  980.54   250.7  981.46
     269  992.25     283  996.82   301.5 1011.08   320.3 1018.65   338.2  1022.4
   381.5 1028.19   393.1 1030.83   406.8  1035.4     416 1035.95   429.9 1034.98
#Mann= 3 ,-1,0
       0      .1       0   208.9    .045       0  222.98      .1       0
Bank Sta=208.9,222.98
XS Rating Curve= 0 ,0
Exp/Cntr(USF)=0,0
Exp/Cntr=0.3,0.1

Type RM Length L Ch R = 1 ,16498   ,297.6,298,297.8
XS GIS Cut Line= 6
 1662069.3056505552310.3769759241661997.82121342552360.837176844
1661936.54902625552404.0887307521661851.60726701552459.170313507
1661776.12775917552491.8096839191661686.82446009552529.227916166
#Sta/Elev= 30
       0  1065.6    32.1 1050.47    58.2 1040.46    65.2 1036.76    76.3 1033.67
    96.4 1023.97   128.8 1012.81   140.6 1005.66   151.9  996.21   168.5  984.31
  203.14 966.454   211.5  965.22   220.5966.4523   232.9  967.73   246.7  967.47
   258.4  969.37   281.2  969.62   301.8  978.45   312.5  979.84   323.6  979.53
   326.8  980.57   337.5  986.75   344.7  989.43   358.9  989.91   362.5  991.31
     366  994.39   373.1 1003.72   376.7 1006.41   412.3 1024.09   442.8 1036.73
#Mann= 3 ,-1,0
       0      .1       0  203.14    .045       0   220.5      .1       0
#XS Ineff= 2 , 0
                          261.73          976.93
Permanent Ineff=
       F       F
Bank Sta=203.14,220.5
XS Rating Curve= 0 ,0
Exp/Cntr(USF)=0,0
Exp/Cntr=0.3,0.1

Type RM Length L Ch R = 1 ,16200   ,296.9,301.3,303.1
XS GIS Cut Line= 6
 1661903.2590666552077.1146471651661829.83598509552124.709696338
1661766.90205584 552165.505546511661682.98982209552219.900122762
1661620.05589284552260.6959729191661546.63313942552308.291350171
#Sta/Elev= 30
       0 1050.68     5.4  1046.3    12.3 1042.56    32.8 1036.49    44.5 1031.83
    60.2 1028.37    71.9 1023.05    91.5  1017.5   114.9 1009.44   119.1  1007.1
     138  988.03   150.1  977.43     154  975.45   167.7  971.59   185.8  962.02
  190.85960.4988   200.9  959.77   221.8960.4978   230.6  963.64   275.6  966.17
   280.4  967.84   288.3  972.55   304.1  974.16     326  985.68   334.9  988.93
   346.8  995.62   370.5 1006.78   384.7 1012.45   408.5 1020.21     425 1027.39
#Mann= 3 ,-1,0
       0      .1       0  190.85    .045       0   221.8      .1       0
Bank Sta=190.85,221.8
XS Rating Curve= 0 ,0
Exp/Cntr(USF)=0,0
Exp/Cntr=0.3,0.1

Type RM Length L Ch R = 1 ,15899   ,367.2,369.2,365.9
XS GIS Cut Line= 6
 1661798.6762705551857.506162509 1661715.6882475551885.253482342
1661644.78550218551909.7032365951661549.40019426551939.842940092
 1661476.5532271551960.1119284181661394.36539935551994.905165926
#Sta/Elev= 30
       0 1041.34      11 1036.26      26 1030.96    43.3 1026.38    53.7  1024.9
    67.5 1020.51    77.9 1018.51     116 1006.91   133.4 1000.29   140.3  996.47
   174.9  971.49   192.1  960.86     199  955.83  201.83954.7869   209.3  953.63
   216.2  953.93  219.37954.7877   223.1  956.09     230  957.05   288.2  957.94
     303  958.76   315.4  960.77   335.9  967.71   346.4  974.07   360.7  979.64
   367.7  983.37   375.7  988.69   382.1  991.37   396.3 1001.69   427.4 1013.76
#Mann= 3 ,-1,0
       0      .1       0  201.83    .045       0  219.37      .1       0
#XS Ineff= 2 , 0
                          272.92           963.8
Permanent Ineff=
       F       F
Bank Sta=201.83,219.37
XS Rating Curve= 0 ,0
Exp/Cntr(USF)=0,0
Exp/Cntr=0.3,0.1