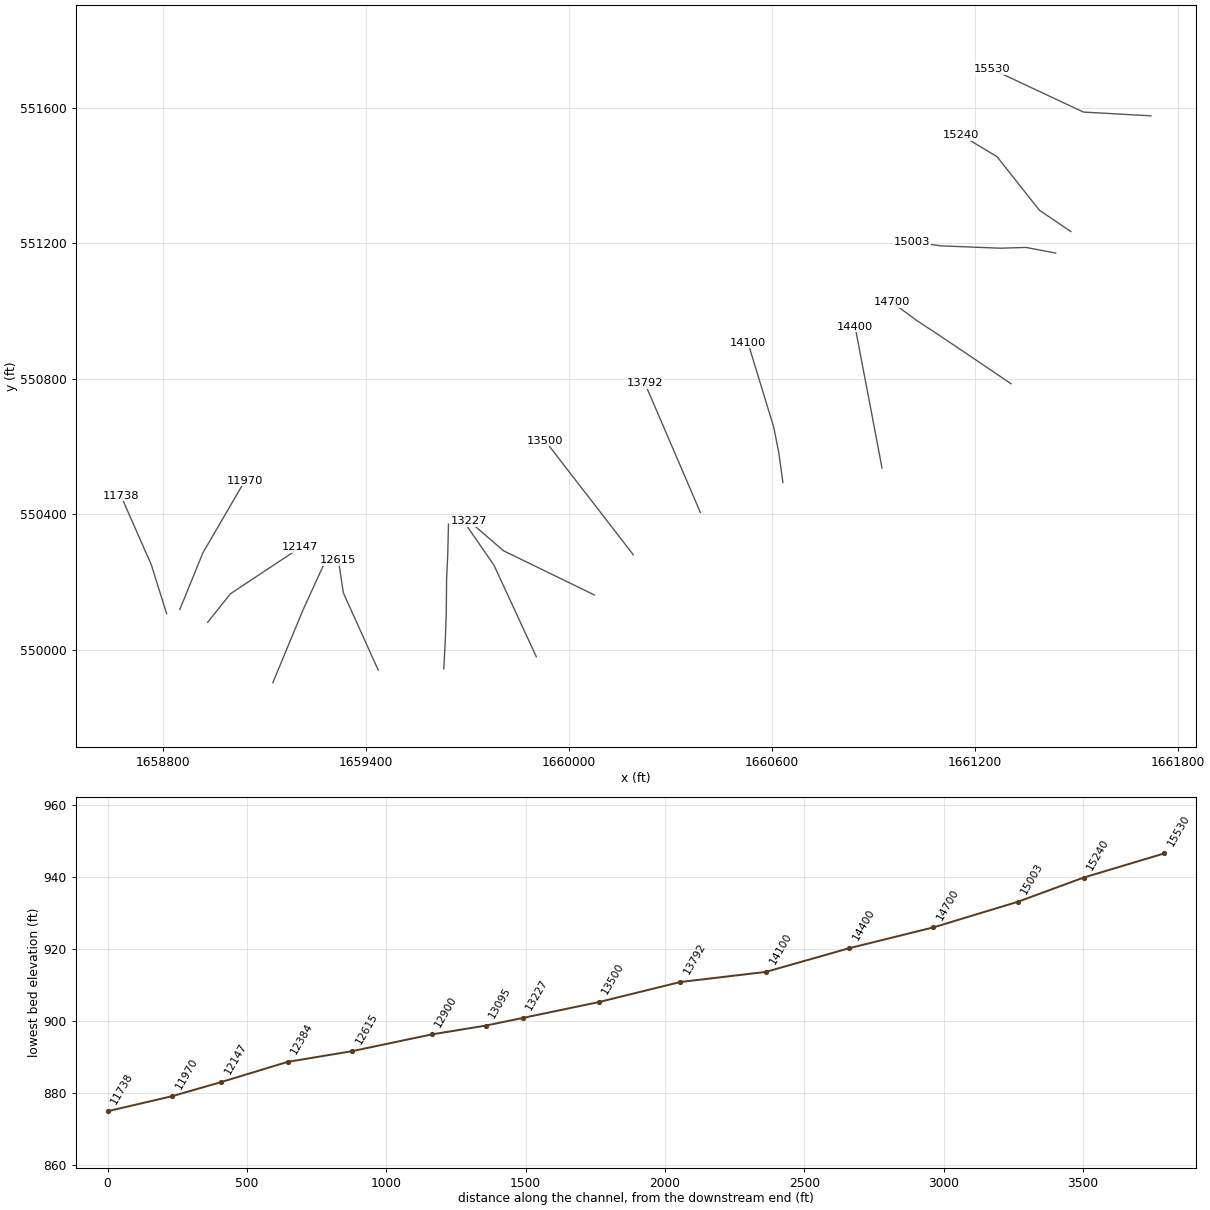
HEC-RAS study GrandstaffRn.prj: GrandstaffRn

--- GrandstaffRn.g01 (geometry) --- (continued)

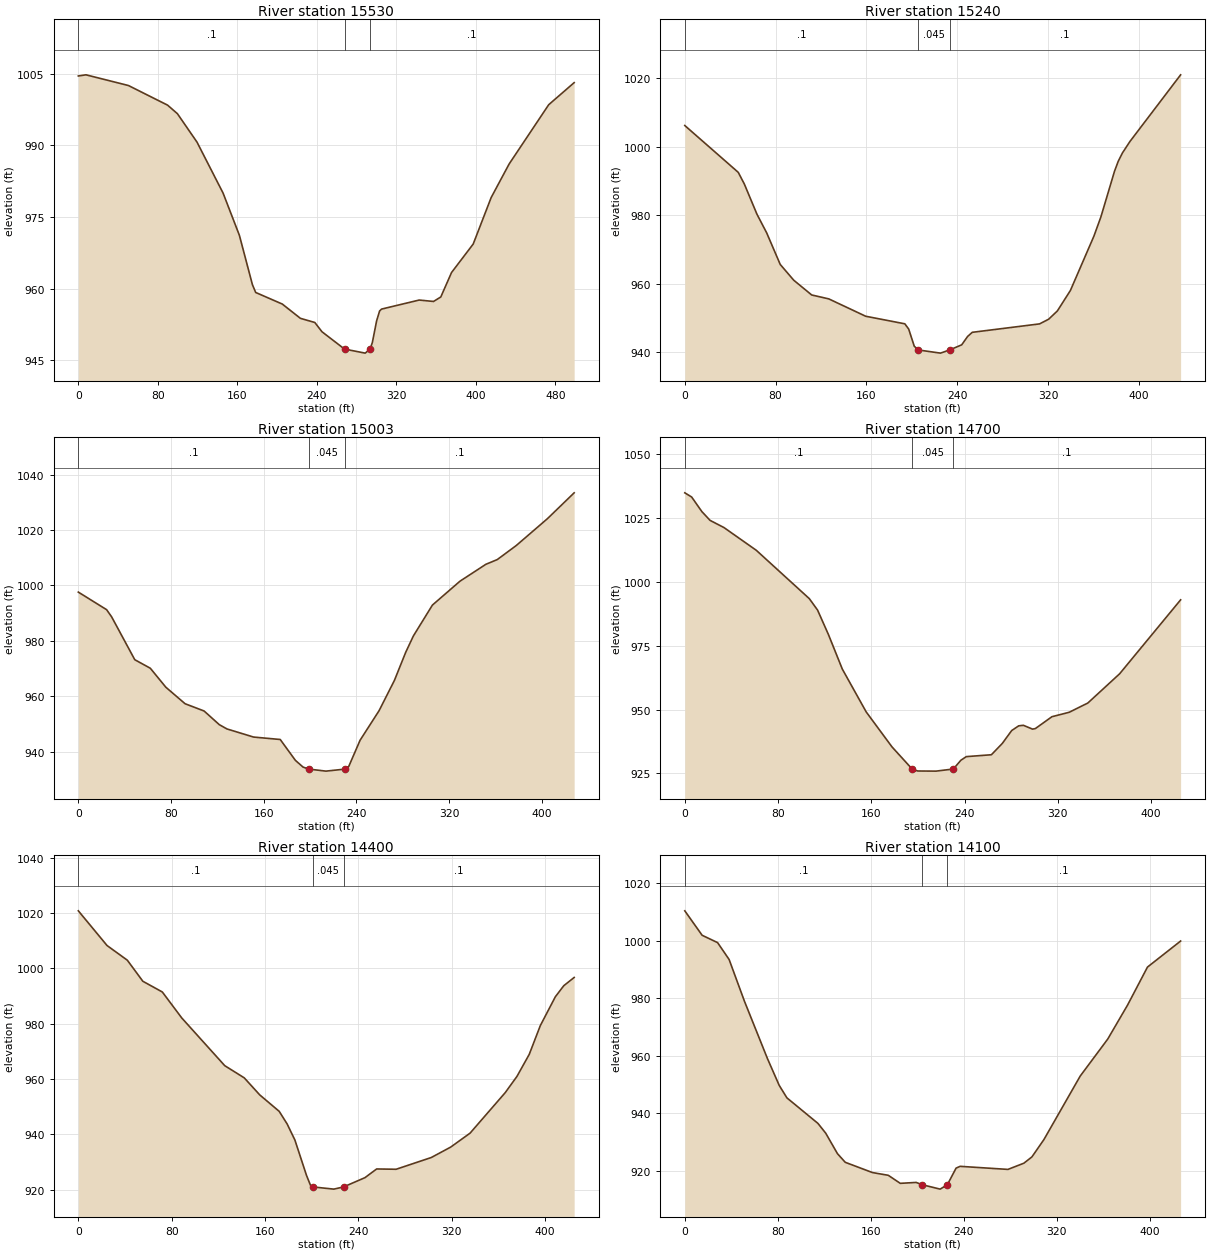
Type RM Length L Ch R = 1 ,15530   ,296.4,289.8,284.3
XS GIS Cut Line= 3
1661719.34594236551575.8955866231661520.02605073551586.965522503
1661248.88236483551713.977707393
#Sta/Elev= 30
       0 1004.56     7.7  1004.8    50.4 1002.56    89.8  998.45    99.7  996.66
   119.4  990.71   145.7  980.01   162.1  971.16   175.2  960.83   178.5  959.19
   205.3  956.76   223.5  953.77     238   952.9   245.2  950.96  267.91947.3282
   288.7  946.48  293.63 947.325   295.9   948.7   300.2  953.25   303.2  955.31
   305.2  955.71     343   957.6   357.5  957.31   364.8  958.25   375.6  963.37
   397.4  969.34   415.5  979.09   433.6  986.13   473.4  998.54     499 1003.16
#Mann= 3 ,-1,0
       0      .1       0  267.91    .045       0  293.63      .1       0
Bank Sta=267.91,293.63
XS Rating Curve= 0 ,0
Exp/Cntr(USF)=0,0
Exp/Cntr=0.3,0.1

Type RM Length L Ch R = 1 ,15240   ,220.5,236.3,245.9
XS GIS Cut Line= 4
1661482.78132738551234.273861106 1661390.0768058551297.036885251
1661264.66608282551455.3944930781661159.34111182551518.718210105
#Sta/Elev= 30
       0 1006.16    47.1   992.5    52.4  989.14    63.6  980.28    72.2  974.81
    84.1  965.63      96  961.03   111.8  956.73   126.9  955.58   159.4  950.52
   193.9  948.31   197.3  946.77   202.2  941.77  205.84940.6815   225.3  939.76
   233.3  940.68     244  942.18   249.2  944.62   253.3  945.83   312.6  948.29
   320.6  949.65   328.3  952.07   339.8  958.05   360.5  973.89   366.6  979.45
   378.6  992.77   381.9  995.71   385.7   998.2   392.3 1001.53   436.9 1020.95
#Mann= 3 ,-1,0
       0      .1       0  205.84    .045       0   233.3      .1       0
Bank Sta=205.84,233.3
XS Rating Curve= 0 ,0
Exp/Cntr(USF)=0,0
Exp/Cntr=0.3,0.1

Type RM Length L Ch R = 1 ,15003   ,311.1,303.6,292.5
XS GIS Cut Line= 5
1661438.05855343551170.6883104291661350.56069693551187.340836167
1661275.59529567551185.0695152581661100.31644675551191.888399258
1661012.81498134551203.703008175
#Sta/Elev= 30
       0   997.6    24.4  991.26    28.7   988.7    48.7  973.22    62.1  970.14
    75.5   963.3    92.1  957.34   108.5  954.72   121.6   949.8   128.2  948.25
   151.2  945.32   174.2  944.44   187.3  936.91   193.9  934.49  198.75933.7708
   213.6  933.03   230.4933.7711   233.3   934.7   243.1  944.17   259.5  954.84
   272.7  965.74   282.5  975.92   289.1   981.8   305.5  992.92   329.3 1001.54
   351.6 1007.62   361.5 1009.34   377.9 1014.42   404.7 1024.07   427.8 1033.41
#Mann= 3 ,-1,0
       0      .1       0  198.75    .045       0   230.4      .1       0
Bank Sta=198.75,230.4
XS Rating Curve= 0 ,0
Exp/Cntr(USF)=0,0
Exp/Cntr=0.3,0.1

Type RM Length L Ch R = 1 ,14700   ,311,300,286.4
XS GIS Cut Line= 6
1661306.44267492550784.8157225851661233.91886984550833.770021006
1661171.75528026550875.7305670081661088.74429142550931.490954176
1661026.00524367550972.5988115821660955.57953151551025.020950839
#Sta/Elev= 30
       0 1034.96     5.9 1033.31    14.6 1027.63    21.7 1024.16    33.6 1021.35
    61.3 1012.45   106.8   993.5   113.9  989.01   123.3  979.33   135.1  965.91
   155.6  949.11   177.7  935.42  194.98926.7419   199.8  925.96   215.5  925.91
  230.36926.7402   236.8  930.17   241.5  931.59     263  932.33   272.3  936.74
   280.4  941.81   286.4  943.65   290.4  943.87   298.3  942.37   300.7  942.58
   314.9  947.23   329.7  948.97   345.7  952.59     373  964.06   425.3  993.03
#Mann= 3 ,-1,0
       0      .1       0  194.98    .045       0  230.36      .1       0
Bank Sta=194.98,230.36
XS Rating Curve= 0 ,0
Exp/Cntr(USF)=0,0
Exp/Cntr=0.3,0.1

Type RM Length L Ch R = 1 ,14400   ,298.2,299.9,300.1
XS GIS Cut Line= 6
1660924.92112826550535.8844619241660908.63769625550621.852465838
1660894.67742234550695.5396544191660875.85068834 550793.75205642
1660861.75590026 550867.418247671660845.37601176550953.375424832
#Sta/Elev= 30
       0 1020.78    24.6 1008.24      42 1002.93    55.3  995.32      72  991.44
    88.7  982.03   125.5  964.81   142.2  960.41   155.5  954.24   172.2  948.29
     179  943.72   185.6  937.97   195.6  925.13   198.9  921.67  201.02920.9773
     219  920.18  227.37920.9779   245.7  924.33   255.7  927.47   272.4  927.36
   302.5   931.6   319.2  935.38   335.8  940.42     366   955.1     376  960.95
   386.5  968.89     396   979.3   408.9  989.73   416.1  993.71     425  996.69
#Mann= 3 ,-1,0
       0      .1       0  201.02    .045       0  227.37      .1       0
Bank Sta=201.02,227.37
XS Rating Curve= 0 ,0
Exp/Cntr(USF)=0,0
Exp/Cntr=0.3,0.1

Type RM Length L Ch R = 1 ,14100   ,305.6,307.7,308.7
XS GIS Cut Line= 6
1660632.22847217550493.4629588431660619.95487468 550581.11599876
1660605.42996934550655.097478092 1660576.2495815550750.745252669
1660554.36379851550822.4810015861660528.83071309550906.172763333
#Sta/Elev= 30
       0  1010.4    14.9  1001.9    28.2  999.34    38.1  993.48    51.4  978.85
    71.1  958.98    81.2  949.67    87.8  945.34   114.5  936.45   121.2  933.04
   131.3  925.91     138  922.91   161.4  919.34     175  918.39   185.3  915.59
     199  915.91  204.14915.1145   219.6  913.58  225.81915.1138   233.3  920.89
   236.8  921.51   277.9  920.44   291.6   922.6   298.5  924.78   308.8   930.8
   340.1  952.94   363.7  965.77   380.8  977.63   397.9  990.83   426.4  999.89
#Mann= 3 ,-1,0
       0      .1       0  204.14    .045       0  225.81      .1       0
Bank Sta=204.14,225.81
XS Rating Curve= 0 ,0
Exp/Cntr(USF)=0,0
Exp/Cntr=0.3,0.1

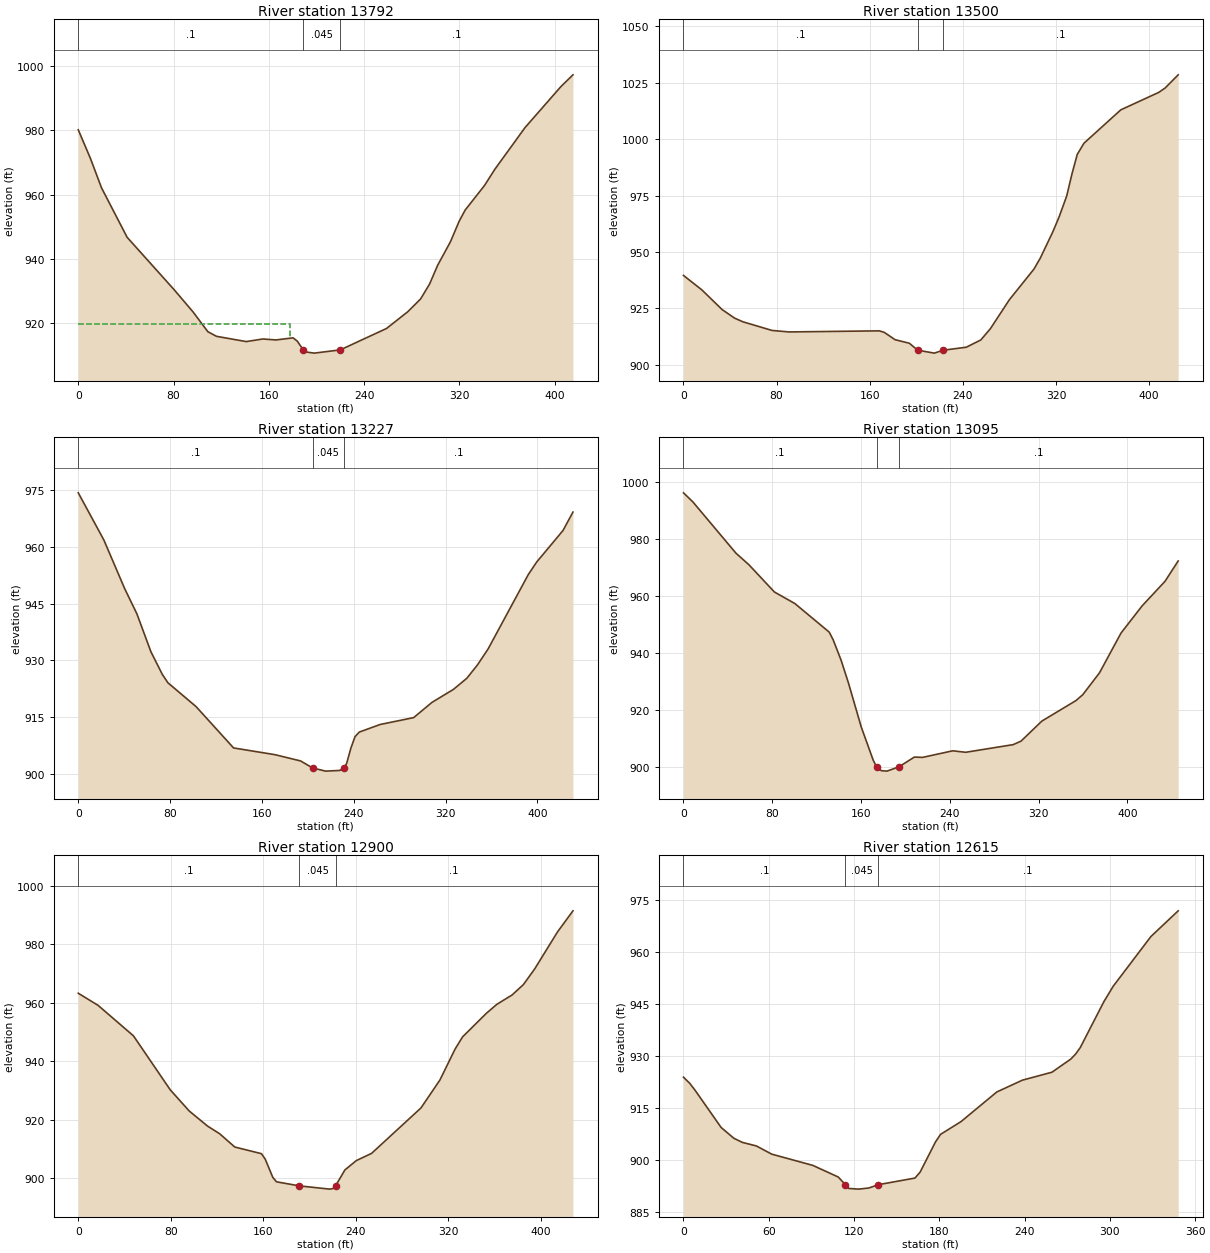
Type RM Length L Ch R = 1 ,13792   ,289.2,292.3,294.7
XS GIS Cut Line= 2
1660388.20079484550404.9829012961660224.15638343550786.513352129
#Sta/Elev= 30
       0  980.21    10.2  971.33    19.5  962.18      41  946.79    80.3  930.56
    96.3   923.6   108.8  917.42     116  915.99     141  914.35     155  915.16
     166  914.86   180.3  915.51   183.8  914.52   188.9911.7682     191  911.13
   198.1  910.76  219.98  911.77   258.8  918.43   276.7  923.66   287.4  927.62
   294.9  932.22   301.7  938.08   312.4  945.36   319.8  951.81   324.8  955.25
     341  962.87   349.8  967.98   375.1  980.92   405.2  993.66   415.3  997.31
#Mann= 3 ,-1,0
       0      .1       0   188.9    .045       0  219.98      .1       0
#XS Ineff= 2 , 0
          177.62  919.97
Permanent Ineff=
       F       F
Bank Sta=188.9,219.98
XS Rating Curve= 0 ,0
Exp/Cntr(USF)=0,0
Exp/Cntr=0.3,0.1

Type RM Length L Ch R = 1 ,13500   ,268.3,273.2,279.9
XS GIS Cut Line= 6
1660190.02003901550280.0388450031660136.50505418550349.266396835
1660090.59241635550408.5707401781660029.37501909550487.643088594
1659983.46238126550546.947431922 1659929.8965435550616.135613754
#Sta/Elev= 30
       0  939.63    15.8  933.21    33.2  924.49    43.9   920.7    50.9   919.1
    76.1  915.24    90.6  914.58   168.2  915.06   172.4  914.42   181.8  911.14
     194  909.58  201.24906.4858   215.5  905.19  223.18906.4852   242.9   907.8
   255.4  911.01   263.7  916.05     280  928.87   301.1  942.44   306.6  947.35
   317.3  958.94   322.7  965.56   329.2  974.78   333.8  984.72   338.3  993.27
   344.1  998.24   375.7 1013.01   408.4 1020.77   413.8 1022.69     425 1028.53
#Mann= 3 ,-1,0
       0      .1       0  201.24    .045       0  223.18      .1       0
Bank Sta=201.24,223.18
XS Rating Curve= 0 ,0
Exp/Cntr(USF)=0,0
Exp/Cntr=0.3,0.1

Type RM Length L Ch R = 1 ,13227   ,137.2,132.1,122.9
XS GIS Cut Line= 3
1660074.90445559 550161.454764591659806.76060248550291.743729484
1659706.03577076550378.470406666
#Sta/Elev= 30
       0  974.23    22.3  961.78    40.5   948.9    51.1  942.28    63.3  932.28
    73.2  926.32    78.1   924.1   102.6  917.82   135.3   906.9   171.4  905.12
   193.7  903.47  204.12901.6234   215.5  900.78   227.8  900.96  231.36901.6204
   233.8   902.8   237.6  906.93   241.1  909.87   244.8  911.08     263  913.09
   292.2   914.9   308.1  918.91   326.9  922.36   338.5  925.28   347.8  928.81
   357.1  933.04     392  952.61   399.3  955.93   422.3  964.28     431  969.15
#Mann= 3 ,-1,0
       0      .1       0  204.12    .045       0  231.36      .1       0
Bank Sta=204.12,231.36
XS Rating Curve= 0 ,0
Exp/Cntr(USF)=0,0
Exp/Cntr=0.3,0.1

Type RM Length L Ch R = 1 ,13095   ,196.4,194.3,188.3
XS GIS Cut Line= 3
1659903.44897531549979.0090493571659778.45061979550249.236210491
1659694.25751256550370.877172161
#Sta/Elev= 30
       0  996.31     8.4  993.15    47.3  975.13      59  971.06    81.9  961.52
   100.3  957.48   131.3  947.44   134.9  944.71   142.1  937.48   148.7  929.51
   160.2   914.1     171  902.45   173.9 900.165   178.3  898.82   183.3  898.67
  194.11900.1626     208   903.6   215.4  903.49   242.6   905.8   254.2  905.28
     297  907.96   304.1  909.19   322.9  916.23   353.6  923.42   359.7  925.47
   374.8  933.15   394.2  947.11   413.2  956.64   433.8  965.25   445.7   972.4
#Mann= 3 ,-1,0
       0      .1       0   173.9    .045       0  194.11      .1       0
Bank Sta=173.9,194.11
XS Rating Curve= 0 ,0
Exp/Cntr(USF)=0,0
Exp/Cntr=0.3,0.1

Type RM Length L Ch R = 1 ,12900   ,274.7,285.8,288.6
XS GIS Cut Line= 6
1659630.23572551549943.2658964991659634.79805234550032.806399837
1659637.46733834   550107.7872211659638.42632592 550207.78734909
1659641.94403543550282.7871990951659643.93714167550370.628886923
#Sta/Elev= 30
       0  963.26    17.1  959.12    47.7  948.68    79.5   930.2    95.9  922.96
   111.7   917.8   122.2  915.17   135.3  910.62   158.3  908.35   161.6  906.48
   168.2  900.19   171.4  898.71  191.22897.3163   217.4  896.21   220.7  896.46
  222.35 897.316   230.5  902.79   240.3  905.97   253.5  908.44   296.2  923.99
   312.6  933.56   325.7  944.14   332.2  948.33   352.7  956.37   361.8  959.46
     375  962.67   384.8  966.24   394.6  971.64   414.3  984.28   427.6  991.47
#Mann= 3 ,-1,0
       0      .1       0  191.22    .045       0  222.35      .1       0
Bank Sta=191.22,222.35
XS Rating Curve= 0 ,0
Exp/Cntr(USF)=0,0
Exp/Cntr=0.3,0.1

Type RM Length L Ch R = 1 ,12615   ,243.8,230.9,222.2
XS GIS Cut Line= 5
1659436.27689246 549939.879074271659405.40950013550008.192914019
1659364.19895262 550099.308545451659333.33123221550167.704406032
1659318.82240296550264.678621525
#Sta/Elev= 30
       0  923.82     4.5     922     8.1  920.08    26.5  909.32    35.4  906.23
    41.4  905.03    51.3     904    62.1  901.64      91   898.4   108.9  895.05
  113.94  892.83   116.1  891.77   123.2  891.56   130.5  891.89  136.97892.8284
   162.9  894.75   166.5  896.46   177.3  905.14   180.9  907.34   195.3  911.02
   220.5  919.56   238.5  922.96   259.3  925.25   272.6  929.05   275.9  930.46
   279.2  932.35   295.8  945.56   302.4  950.03   328.9  964.34   348.1  971.75
#Mann= 3 ,-1,0
       0      .1       0  113.94    .045       0  136.97      .1       0
Bank Sta=113.94,136.97
XS Rating Curve= 0 ,0
Exp/Cntr(USF)=0,0
Exp/Cntr=0.3,0.1

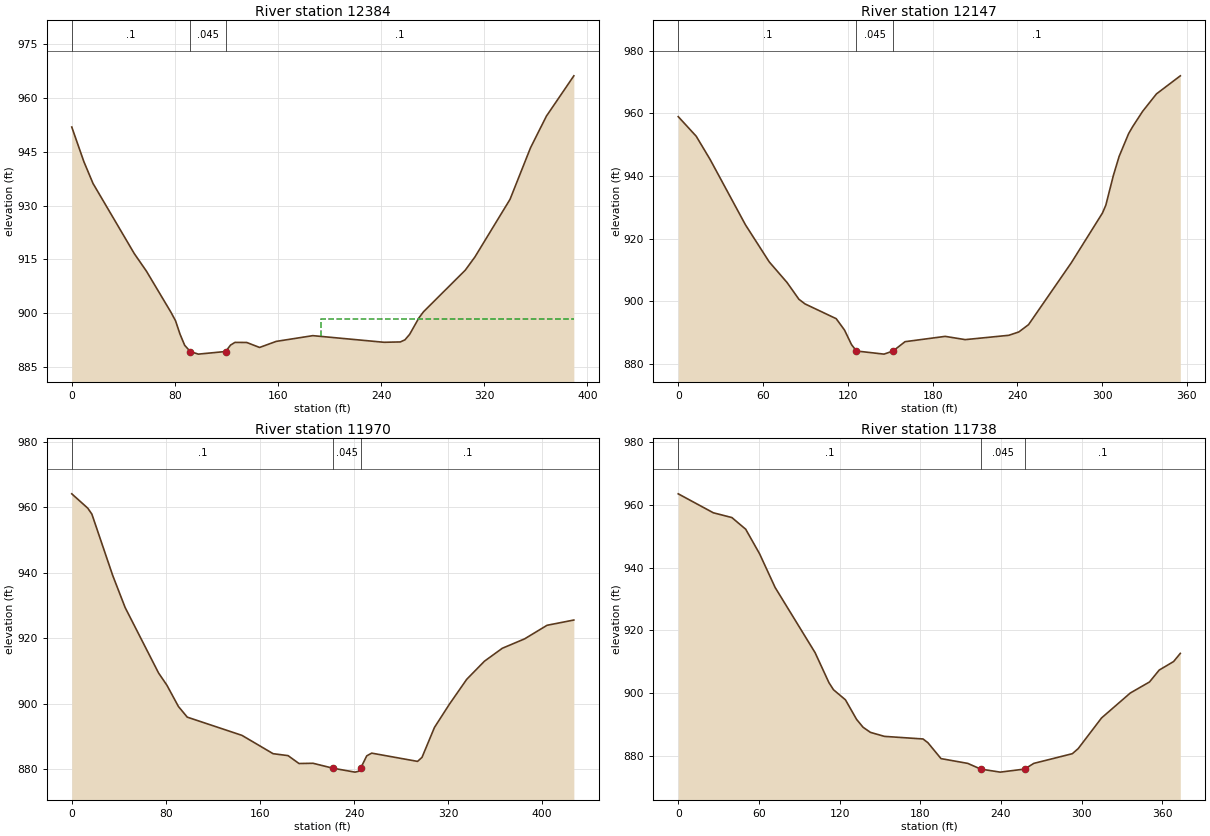
Type RM Length L Ch R = 1 ,12384   ,246,237.3,230.3
XS GIS Cut Line= 3
1659125.07140996549902.4450222021659214.22384406550117.205752865
1659279.64296543550259.898711626
#Sta/Elev= 30
       0  951.89     9.4  942.23    16.5  936.15    48.5  916.61    57.9  911.73
    76.9  900.29    80.5  897.89      84  894.14    87.6  891.05   91.89889.3201
    98.2  888.59  119.36  889.32   123.2  891.12   126.6  891.86   135.7  891.84
   145.7  890.45   158.6  892.14     187  893.74   242.3  891.89   254.9  891.99
   258.5  892.58   262.1   894.1   269.3  898.68   272.9  900.41   305.3     912
   312.8   915.7     340  931.74   355.9  946.11   368.2  954.92   389.5  966.16
#Mann= 3 ,-1,0
       0      .1       0   91.89    .045       0  119.36      .1       0
#XS Ineff= 2 , 0
                          193.21          898.44
Permanent Ineff=
       F       F
Bank Sta=91.89,119.36
XS Rating Curve= 0 ,0
Exp/Cntr(USF)=0,0
Exp/Cntr=0.3,0.1

Type RM Length L Ch R = 1 ,12147   ,167.9,176.8,179.2
XS GIS Cut Line= 3
1658932.62012427550080.550285663 1658999.5766967550164.724262442
 1659206.1855488550301.506974707
#Sta/Elev= 30
       0  958.99    12.7  952.74    22.5  945.34    47.6  924.36    64.4  912.52
      77  905.93    85.4  900.56    89.7  899.08   111.8  894.35   117.7  890.69
   122.6  886.07  126.11884.0124   145.6  883.01  152.02884.0125   160.5  886.99
   188.9  888.69   203.1  887.65   233.9  889.03     241   890.1   247.9  892.44
   278.2  912.26   300.2  928.15   302.6  930.67   307.9  940.12     312  946.27
   318.7  953.54   321.5  955.73   328.6  960.67   338.4  966.26   355.3  972.05
#Mann= 3 ,-1,0
       0      .1       0  126.11    .045       0  152.02      .1       0
Bank Sta=126.11,152.02
XS Rating Curve= 0 ,0
Exp/Cntr(USF)=0,0
Exp/Cntr=0.3,0.1

Type RM Length L Ch R = 1 ,11970   ,213.1,231.7,240.8
XS GIS Cut Line= 3
1658850.13427032550118.4017520181658918.38356856550285.631162035
1659042.41453512550498.410460961
#Sta/Elev= 30
       0  964.06    13.6  959.68    17.1  957.86    34.8  939.14    45.4  929.32
    73.8  909.35    80.9  905.61    90.7  899.11    98.2  895.86   144.7   890.3
   171.2   884.7   183.9  884.11   193.2   881.7   205.2  881.77  221.98 880.272
   240.8  879.07   243.6   879.3  245.63 880.271   250.8  884.04     255  884.87
     294  882.35   297.8  883.58   308.4  892.73   321.2  899.87   335.8  907.41
   350.9  912.95   366.1   916.9     385  919.76   404.1  923.91   426.9  925.52
#Mann= 3 ,-1,0
       0      .1       0  221.98    .045       0  245.63      .1       0
Bank Sta=221.98,245.63
XS Rating Curve= 0 ,0
Exp/Cntr(USF)=0,0
Exp/Cntr=0.3,0.1

Type RM Length L Ch R = 1 ,11738   ,334.5,337.9,335.6
XS GIS Cut Line= 3
1658811.30256369 550106.039522581658765.86812786550250.825996358
 1658676.4217764550453.775574775
#Sta/Elev= 30
       0  963.46    26.1  957.43    39.9  955.91    50.2  952.19    60.5  944.39
    72.1  933.64   101.8  912.92   112.1  903.38   115.5  901.11   124.4   897.9
   132.7  891.66   137.5  889.17     143  887.54   153.4  886.27   182.1  885.44
   185.7  884.27   195.5  879.19   215.4  877.67  224.97875.8653   239.5  874.89
  257.71875.8643   264.5  877.67   293.2  880.76   297.5  882.36   314.9  892.13
   336.3  900.07   350.6  903.59   357.8  907.37   368.5  910.08   373.5  912.68
#Mann= 3 ,-1,0
       0      .1       0  224.97    .045       0  257.71      .1       0
Bank Sta=224.97,257.71
XS Rating Curve= 0 ,0
Exp/Cntr(USF)=0,0
Exp/Cntr=0.3,0.1