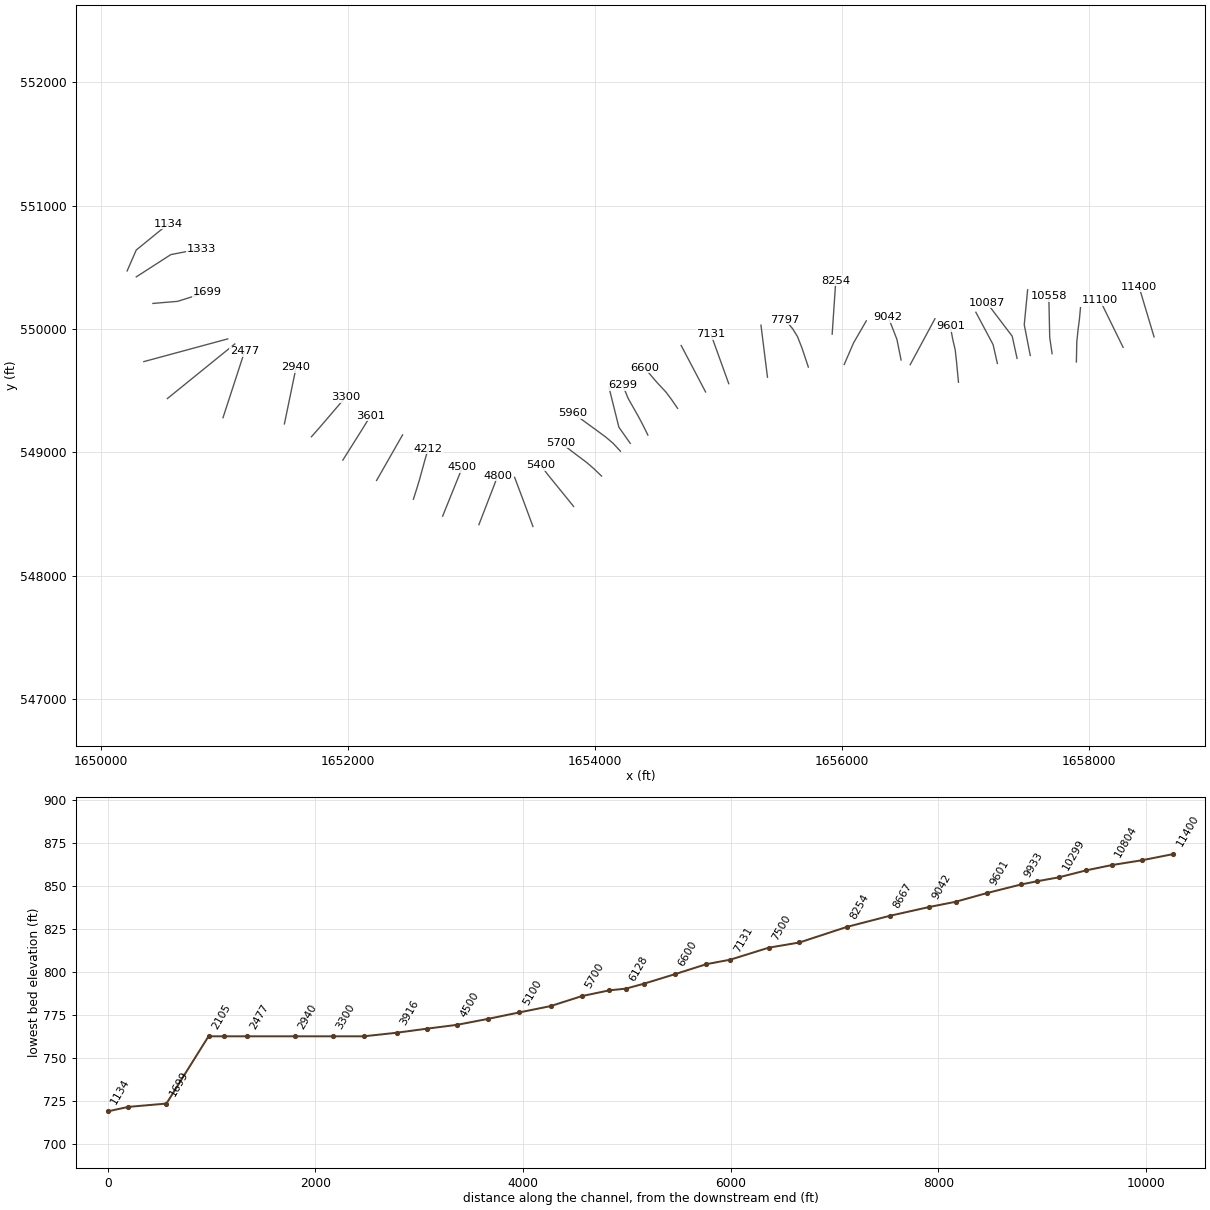
HEC-RAS study GrandstaffRn.prj: GrandstaffRn

--- GrandstaffRn.g01 (geometry) --- (continued)

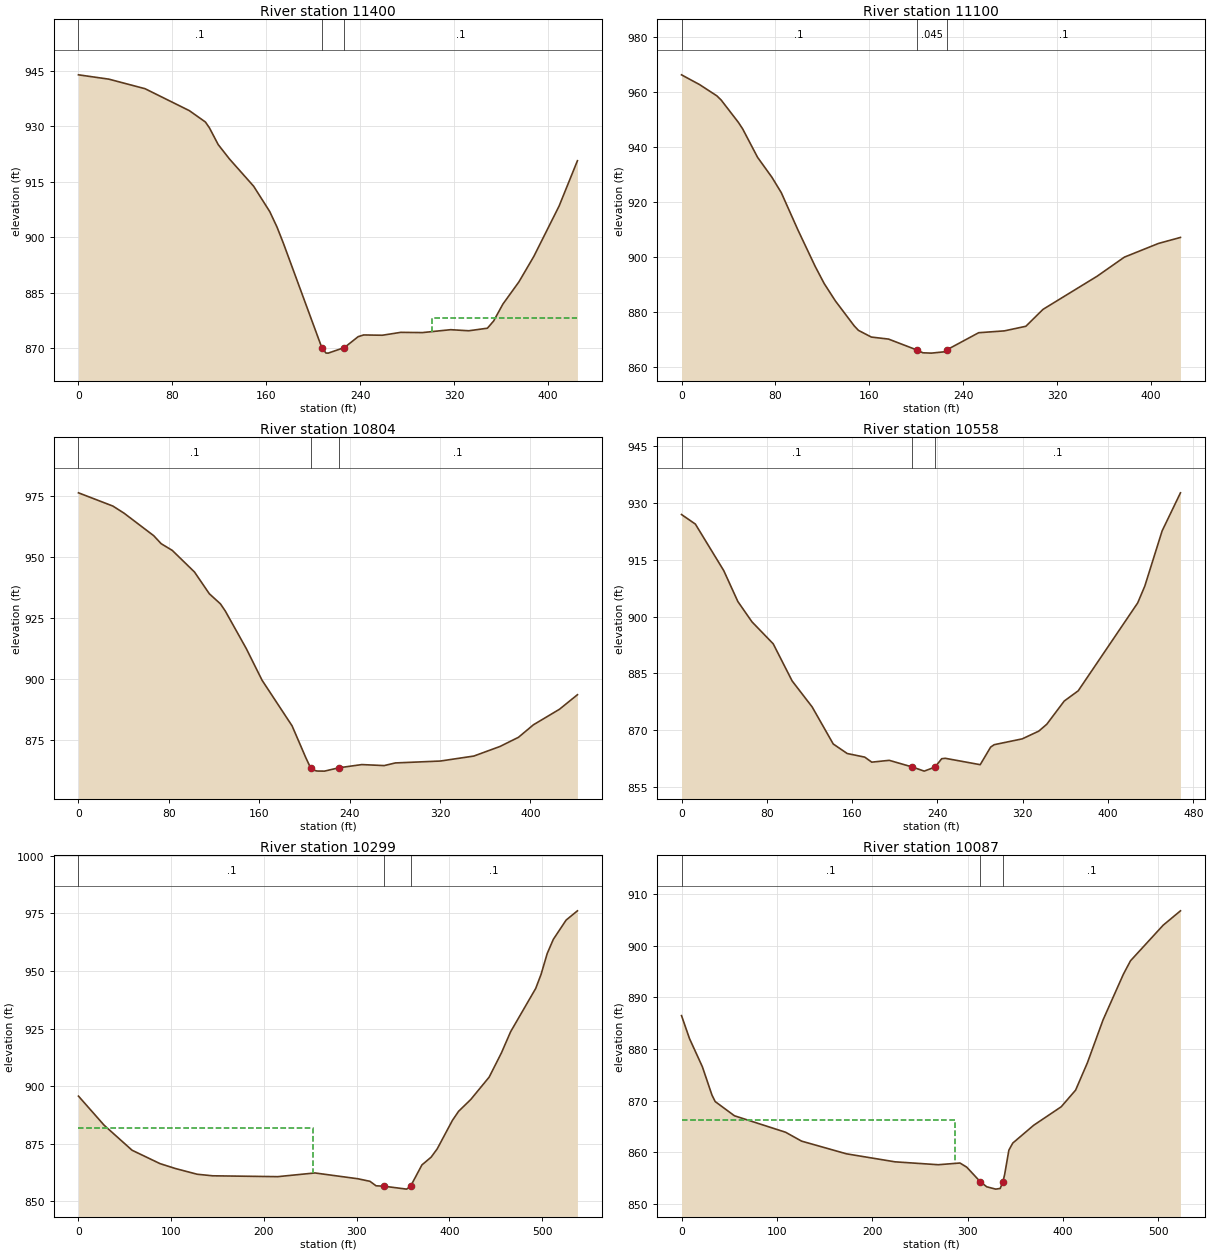
Type RM Length L Ch R = 1 ,11400   ,298.3,300.1,302.2
XS GIS Cut Line= 6
 1658527.9803841549935.5520011781658502.92859693550019.391728505
1658481.40797067550091.2403380871658452.65540351 550187.01770559
1658431.22007893550258.8873125021658406.20963025550342.733601511
#Sta/Elev= 30
       0  943.87    25.9   942.7    56.7  940.12    94.4   934.2   108.1  931.13
   111.5  929.57     119  925.03   128.6  921.14   149.2  913.78   162.9  906.94
   169.1  902.75   174.4  898.49  207.24870.2034   210.8  868.72   212.7   868.7
   226.5870.2023   238.2  873.14   242.9  873.61   258.8  873.53   274.5  874.31
     293  874.25     317  875.03   332.5  874.74   348.3  875.43   353.6  877.37
   361.5  881.94   375.2  887.97   387.9  894.85   409.4  908.44     425  920.67
#Mann= 3 ,-1,0
       0      .1       0  207.24    .045       0   226.5      .1       0
#XS Ineff= 2 , 0
                          300.72          878.16
Permanent Ineff=
       F       F
Bank Sta=207.24,226.5
XS Rating Curve= 0 ,0
Exp/Cntr(USF)=0,0
Exp/Cntr=0.3,0.1

Type RM Length L Ch R = 1 ,11100   ,299.8,295.8,285.9
XS GIS Cut Line= 6
1658277.33226334549851.2801880841658238.77295725549929.825962752
1658205.72282651549997.1509593431658161.65500125550086.917512089
1658128.60552667550154.2431648371658090.79917184550233.158361346
#Sta/Elev= 30
       0  966.31    15.5  962.73    30.1  958.67    33.8  957.13    48.4  949.04
    52.1  946.64    64.8   936.3    77.1     929      85  923.45    99.1  909.95
   113.8   896.7   121.5  890.43     131  884.13   147.1  875.02   150.7  873.39
   161.7  870.95   176.3  870.22  200.21866.3031   205.6  865.23   212.9  865.11
   223.8  865.59  225.99866.3034   253.1  872.53     275   873.2   293.3  874.87
   307.9  881.02   354.1   893.1   377.2  900.01   406.3     905     425  907.18
#Mann= 3 ,-1,0
       0      .1       0  200.21    .045       0  225.99      .1       0
Bank Sta=200.21,225.99
XS Rating Curve= 0 ,0
Exp/Cntr(USF)=0,0
Exp/Cntr=0.3,0.1

Type RM Length L Ch R = 1 ,10804   ,243.8,246.5,244.9
XS GIS Cut Line= 6
1657898.98361059549733.0156608371657900.76904009549820.497113168
1657902.29954883549895.4815432581657912.68961993549995.706736505
1657923.21125242550075.4067083451657932.20303234550173.061040595
#Sta/Elev= 30
       0   976.2    30.5  970.77    40.3  967.88    66.6  958.65    73.2  955.37
      83  952.64   102.7  943.78   115.8  934.89   125.7  930.72     130  927.78
   148.6  912.38   162.5  899.48   189.1  880.79   201.3   867.7   204.6  864.46
  206.25863.6163   207.9   862.7   211.2   862.3   217.8  862.26  230.39863.6177
   250.8  864.94   270.6  864.53   280.5  865.61   320.3  866.39     350  868.43
   373.1  872.35   389.5  876.11   402.7  881.22   425.8  887.59   441.7  893.54
#Mann= 3 ,-1,0
       0      .1       0  206.25    .045       0  230.39      .1       0
Bank Sta=206.25,230.39
XS Rating Curve= 0 ,0
Exp/Cntr(USF)=0,0
Exp/Cntr=0.3,0.1

Type RM Length L Ch R = 1 ,10558   ,249.6,258.9,252.7
XS GIS Cut Line= 3
1657702.43633968 549799.816940671657683.05089515549930.887078414
1657675.76143879550266.202070914
#Sta/Elev= 30
       0  926.95      13  924.42    39.6  912.14    52.8  903.99    66.1   898.6
      86   892.8   103.7  883.02   122.5  876.14   142.3  866.34   155.4  863.83
   171.8  862.88   178.4  861.55   194.8  862.03  216.58860.2592   227.6  859.18
  237.76860.2573     244  862.46   247.3  862.57   280.1  860.88   289.9  865.53
   293.2  866.16   319.5   867.7     335  869.74   342.5  871.55   358.9  877.69
     372  880.39   427.8  903.61   434.5  908.08   450.7  922.63   467.9  932.68
#Mann= 3 ,-1,0
       0      .1       0  216.58    .045       0  237.76      .1       0
Bank Sta=216.58,237.76
XS Rating Curve= 0 ,0
Exp/Cntr(USF)=0,0
Exp/Cntr=0.3,0.1

Type RM Length L Ch R = 1 ,10299   ,196.9,211.5,217.2
XS GIS Cut Line= 3
1657525.42653648549785.4908894011657476.86659034550034.715056524
1657504.19855573550317.609413532
#Sta/Elev= 30
       0  895.61    27.7  882.95    57.8  872.09    87.9  866.28   104.6  864.14
     128  861.66   144.7  860.98   214.9  860.61     255  862.22   301.2   859.7
   314.3  858.59   320.9  856.64  329.57856.4479   353.9  855.19  358.14856.4468
   370.4  865.72   380.3  869.08   386.9  872.71   403.3  885.09   409.9     889
   423.1  894.17   442.9  903.88   456.1  914.39     466  923.57   493.1  942.42
   498.9  948.57   505.5   957.6   512.1  963.76   525.9  972.13   538.1  976.15
#Mann= 3 ,-1,0
       0      .1       0  329.57    .045       0  358.14      .1       0
#XS Ineff= 2 , 0
          253.36  881.75
Permanent Ineff=
       F       F
Bank Sta=329.57,358.14
XS Rating Curve= 0 ,0
Exp/Cntr(USF)=0,0
Exp/Cntr=0.3,0.1

Type RM Length L Ch R = 1 ,10087   ,153.4,154.2,152
XS GIS Cut Line= 3
1657418.71958979549761.828762941 1657379.1195598549941.750638306
1657174.23244814550212.063886463
#Sta/Elev= 30
       0  886.44     8.4  881.99    21.9  876.54    31.9  871.09    35.3  869.82
    55.5  867.07   109.2  863.88     126  862.16     173  859.71     224  858.16
   269.3   857.6   292.1  857.93   299.2  857.13  313.44854.3038   320.2  853.33
   329.6  852.88   334.3  853.01  337.15854.2997     339  855.74   343.4  860.42
   347.5  861.79   369.4  865.23   398.3  868.81   413.4  872.03   425.8  877.33
   442.2  885.62   463.5  894.44     471  897.05   505.2  903.92   523.4  906.71
#Mann= 3 ,-1,0
       0      .1       0  313.44    .045       0  337.15      .1       0
#XS Ineff= 2 , 0
          287.28  866.29
Permanent Ineff=
       F       F
Bank Sta=313.44,337.15
XS Rating Curve= 0 ,0
Exp/Cntr(USF)=0,0
Exp/Cntr=0.3,0.1

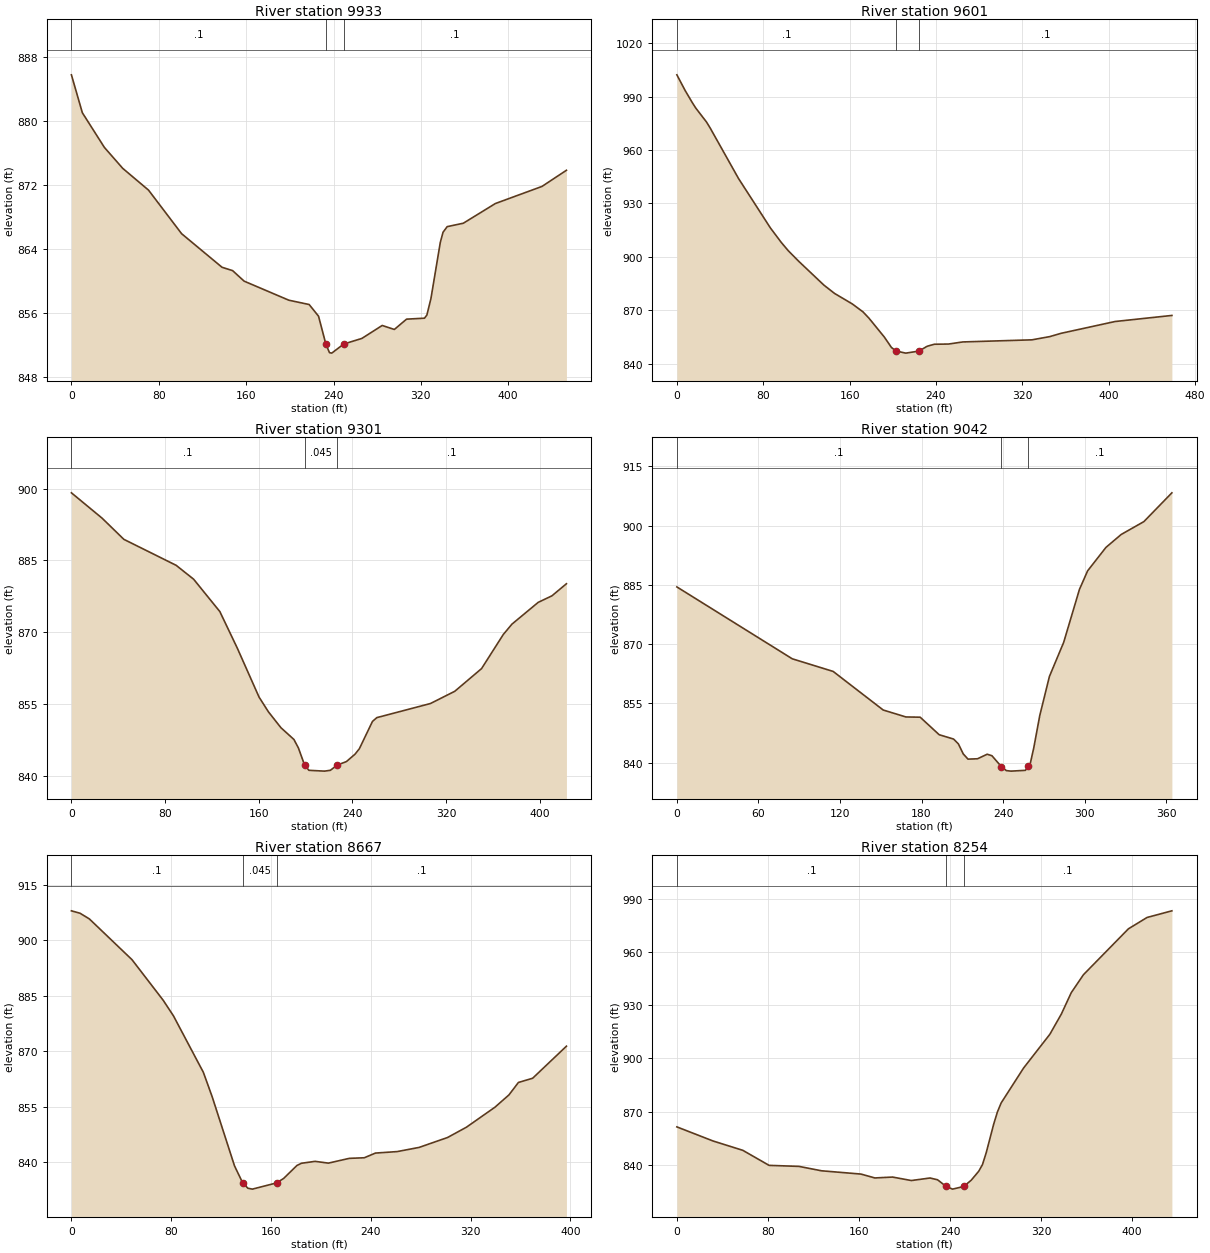
Type RM Length L Ch R = 1 ,9933    ,335,332.2,325.7
XS GIS Cut Line= 3
1657259.21040961549720.9097292311657224.39830106549873.883529689
1657085.10125259550135.475314139
#Sta/Elev= 30
       0  885.82      10  881.08    30.2  876.74      47  874.12    70.6   871.4
   100.9  865.95   137.9  861.75   147.6  861.33   158.2  860.01   199.1  857.63
   217.7  857.09   226.3  855.63  232.98  852.15   236.3  851.07   238.4  851.01
   249.4  852.15     266  852.85   284.6  854.47   295.7  853.97   306.9  855.26
   323.3  855.38   325.5  855.77   329.2  857.82   337.8  864.86   340.3  866.13
   344.1  866.83   358.9  867.26   388.2  869.72   430.9  871.86   453.3  873.88
#Mann= 3 ,-1,0
       0      .1       0  232.98    .045       0   249.4      .1       0
Bank Sta=232.98,249.4
XS Rating Curve= 0 ,0
Exp/Cntr(USF)=0,0
Exp/Cntr=0.3,0.1

Type RM Length L Ch R = 1 ,9601    ,305.2,300.2,292.1
XS GIS Cut Line= 6
1656944.25356467549568.8886924981656935.96519542549655.968898922
1656928.85956658549730.6216367481656917.97277734549830.039088845
1656898.39079551549913.8561784181656877.95809358550021.881880999
#Sta/Elev= 30
       0 1002.18     7.6  993.45    14.2  986.67    17.5  983.53    27.4  975.73
    30.7  972.49    57.1  943.99    86.7  916.18    96.6  908.19   103.2  903.44
   113.1  897.39   136.2  884.14   146.1  879.46   162.5  873.58   172.4  869.12
   177.9  865.61   192.2  854.95   198.8  849.09  203.22847.1187     212  845.97
  224.22847.1173   231.8  849.82   238.4  850.95   251.6  851.07   264.9  852.25
   328.9  853.43   345.4  855.24   355.8  857.08   405.9  863.72   458.5  867.12
#Mann= 3 ,-1,0
       0      .1       0  203.22    .045       0  224.22      .1       0
Bank Sta=203.22,224.22
XS Rating Curve= 0 ,0
Exp/Cntr(USF)=0,0
Exp/Cntr=0.3,0.1

Type RM Length L Ch R = 1 ,9301    ,250.4,258.2,267.5
XS GIS Cut Line= 2
1656553.23715781549710.9129749821656753.71031059550083.272834346
#Sta/Elev= 30
       0  899.15    26.2  893.85    44.8  889.42    89.5  883.98   104.4  881.08
   126.8  874.31   141.7  866.67   160.3  856.42   168.3  853.34     179  850.01
   190.1  847.55   193.9  845.79   199.2842.2056   202.9   841.1   216.2  840.93
   221.2   841.1  227.13 842.206   234.9  842.92   242.3  844.48     246  845.62
   257.2  851.33   260.9  852.12   306.7  855.07   327.5  857.63   350.4  862.38
     369  869.53   376.4  871.69   398.8  876.24   410.5   877.6   422.9  880.13
#Mann= 3 ,-1,0
       0      .1       0   199.2    .045       0  227.13      .1       0
Bank Sta=199.2,227.13
XS Rating Curve= 0 ,0
Exp/Cntr(USF)=0,0
Exp/Cntr=0.3,0.1

Type RM Length L Ch R = 1 ,9042    ,384.7,375.7,363.5
XS GIS Cut Line= 3
1656479.51993572549749.2370464271656445.51024814549917.159878887
1656375.36526749550096.773541456
#Sta/Elev= 30
       0   884.5    84.9  866.29     115  863.09   151.8  853.32   168.5  851.56
     179   851.5     193  847.06   203.6  845.96   207.1  844.75   210.7   842.2
   214.2  840.88   221.2  840.97   228.3  842.12   231.8  841.74  238.67839.0117
   242.4  837.97   245.9  837.84   256.4  838.04  258.53839.0143     260  839.76
   262.6  843.77     267  851.93   274.1  861.82   284.6  870.47   296.2  883.88
   302.2  888.57   315.7  894.51   326.9  897.78   343.6  901.04   364.2  908.33
#Mann= 3 ,-1,0
       0      .1       0  238.67    .045       0  258.53      .1       0
Bank Sta=238.67,258.53
XS Rating Curve= 0 ,0
Exp/Cntr(USF)=0,0
Exp/Cntr=0.3,0.1

Type RM Length L Ch R = 1 ,8667    ,407.2,413.1,403.2
XS GIS Cut Line= 3
1656018.91388984549712.3318700941656094.54562383549887.298664651
 1656197.9079928550065.834509932
#Sta/Elev= 30
       0  908.02     6.9  907.37    14.4  905.83    48.6   894.8    73.6  883.83
    81.8  879.63   105.8  864.35   112.9  857.71   130.8  839.03  137.34834.4501
   141.5  833.01   145.1  832.77  164.46834.4475   170.1  835.64   180.8  839.16
   184.4  839.76   195.4  840.28     206   839.8   222.8  841.09   234.8  841.25
   243.8  842.52   261.2  842.92   278.8  844.05   301.6  846.73   316.7  849.51
   339.5   854.9   350.8  858.24   358.4  861.61   369.8  862.75   396.9  871.42
#Mann= 3 ,-1,0
       0      .1       0  137.34    .045       0  164.46      .1       0
Bank Sta=137.34,164.46
XS Rating Curve= 0 ,0
Exp/Cntr(USF)=0,0
Exp/Cntr=0.3,0.1

Type RM Length L Ch R = 1 ,8254    ,449.8,456.3,452.9
XS GIS Cut Line= 2
1655921.55912678549958.2372046761655950.82871416550392.115794067
#Sta/Elev= 30
       0  861.41    31.7  853.48      58  848.18      81  839.72   107.3  839.13
   127.1  836.66   161.7  834.81     174  832.62   189.5  833.12     206  831.16
   222.4  832.59     229   831.6  236.65827.8165   242.2  826.32  252.07827.8173
   258.6  831.35   265.2   836.4   268.5  840.16   271.8   846.9   278.3  862.85
   281.6  869.79   284.9  874.91   304.6  894.59   327.7  913.63   337.8  925.05
   346.5  937.08   357.2   947.2   396.7  973.07   413.1  979.48   434.9  983.22
#Mann= 3 ,-1,0
       0      .1       0  236.65    .045       0  252.07      .1       0
Bank Sta=236.65,252.07
XS Rating Curve= 0 ,0
Exp/Cntr(USF)=0,0
Exp/Cntr=0.3,0.1

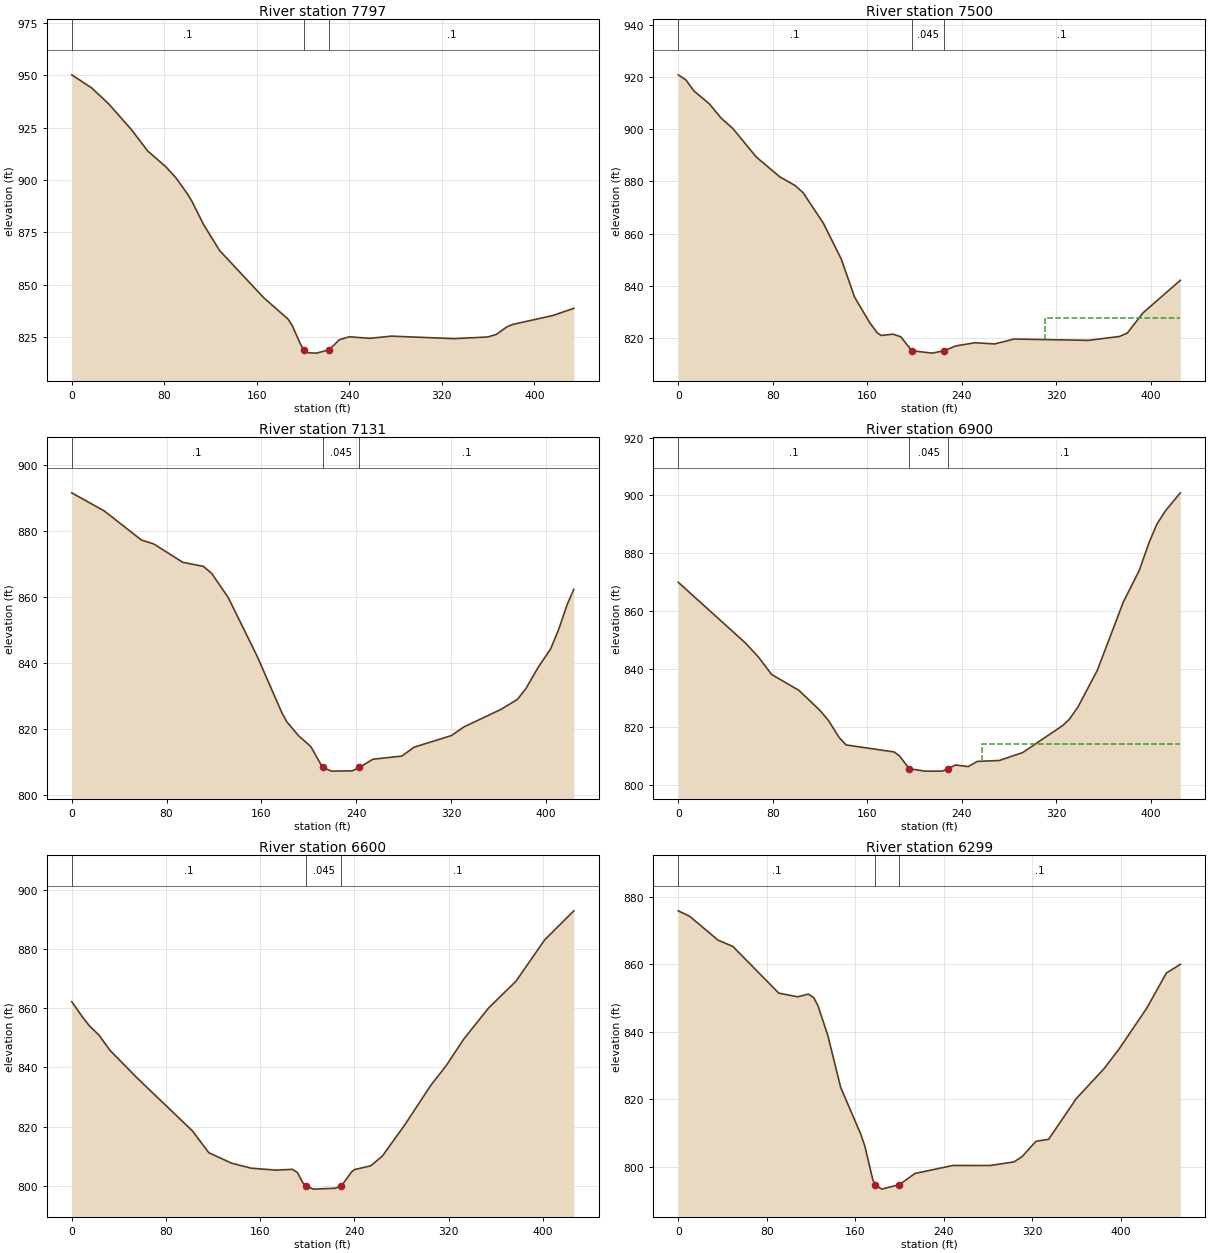
Type RM Length L Ch R = 1 ,7797    ,300.5,297.3,294.4
XS GIS Cut Line= 6
1655728.67463101549691.4045235961655701.00473884549774.414200082
1655677.28792275549845.5656325821655640.58359984549938.739986926
1655600.26937601550003.6581641731655538.61694026550076.137678012
#Sta/Elev= 30
       0   950.2    17.2  943.95      32  936.29    51.8  923.89    65.6  913.88
    81.3   906.3    89.8  901.22   100.2  893.24   103.7  890.02     114  878.68
   127.9  866.24     166  843.75     187  833.56   190.7  830.39   197.7  821.68
  200.44818.9635   204.5  817.44   211.8  817.28  222.86818.9628   231.3  823.65
     240  825.09   257.7  824.34   276.5   825.4   330.6  824.19   359.7  824.99
     367  826.17   376.3  829.81   381.3  830.99   415.9  835.22   434.2  838.68
#Mann= 3 ,-1,0
       0      .1       0  200.44    .045       0  222.86      .1       0
Bank Sta=200.44,222.86
XS Rating Curve= 0 ,0
Exp/Cntr(USF)=0,0
Exp/Cntr=0.3,0.1

Type RM Length L Ch R = 1 ,7500    ,366,369,372.7
XS GIS Cut Line= 6
1655397.72975484549609.3243071731655386.87643009549696.148608595
1655377.57428335549770.5697195831655365.17043675549869.797539502
1655355.86796193549944.2183224261655345.01463717550031.042623833
#Sta/Elev= 30
       0  920.78     6.6  918.79    13.2  914.65    26.4  909.64    36.3  904.21
    46.3   900.2    66.1   889.3    85.9  881.75    99.2  878.32   105.8  875.59
   122.9  863.95     138  850.25   149.3  835.64     162  825.96   168.6  821.91
   171.9     821   181.8  821.49   188.4  820.48   197.8815.1364   214.9  814.23
  225.09815.1356   234.7  816.96   251.2  818.21   267.8  817.75   284.3  819.62
   347.1  819.12   373.6  820.61   380.2  821.93   393.4  829.63     425  842.11
#Mann= 3 ,-1,0
       0      .1       0   197.8    .045       0  225.09      .1       0
#XS Ineff= 2 , 0
                          310.83          827.77
Permanent Ineff=
       F       F
Bank Sta=197.8,225.09
XS Rating Curve= 0 ,0
Exp/Cntr(USF)=0,0
Exp/Cntr=0.3,0.1

Type RM Length L Ch R = 1 ,7131    ,228.9,231,233.1
XS GIS Cut Line= 2
1655084.12014584549557.2932432591654940.26873096549955.840377026
#Sta/Elev= 30
       0  891.48    27.4  886.01    58.8  877.19    69.2  876.01    93.7  870.46
   111.1  869.23   118.1  867.09     132  859.83   156.4  842.08   177.4  824.87
   181.3  822.31   191.3  818.02   201.8  814.69  211.63808.3859   219.2  807.28
   236.7  807.37  242.63 808.386   254.1  810.88   278.5  811.83     289  814.54
   320.4  818.04   330.8  820.63   362.2  825.96   376.2  829.02   383.2  832.24
   393.6  838.68   404.1  844.25   411.1  850.34     418  857.62   423.7   862.3
#Mann= 3 ,-1,0
       0      .1       0  211.63    .045       0  242.63      .1       0
Bank Sta=211.63,242.63
XS Rating Curve= 0 ,0
Exp/Cntr(USF)=0,0
Exp/Cntr=0.3,0.1

Type RM Length L Ch R = 1 ,6900    ,295.2,299.7,303.5
XS GIS Cut Line= 6
1654896.47649226549490.1231020091654855.80334526 549567.59538801
 1654820.9405541549634.0001108351654774.45737934549722.539960012
1654739.59491625549788.9446828371654698.92176926549866.416968837
#Sta/Elev= 30
       0  869.99    56.8  849.02    68.1  844.03      79  838.11   102.1  832.61
   119.8  825.75   127.2  822.16   136.1  816.36     142  813.73   182.8  811.29
   187.2  809.95  195.62805.4823   208.7  804.66   223.5  804.66  228.52 805.485
   234.7  806.78   245.5  806.24   253.2  808.02   271.7  808.34   291.6  811.08
   325.7  820.51     331  822.57   338.4  826.87   354.8  839.58   376.7  863.09
   390.3  874.14   398.5  883.67   405.1  890.03   412.5  894.75     425  900.92
#Mann= 3 ,-1,0
       0      .1       0  195.62    .045       0  228.52      .1       0
#XS Ineff= 2 , 0
                           257.4          813.91
Permanent Ineff=
       F       F
Bank Sta=195.62,228.52
XS Rating Curve= 0 ,0
Exp/Cntr(USF)=0,0
Exp/Cntr=0.3,0.1

Type RM Length L Ch R = 1 ,6600    ,302.3,301.2,298.5
XS GIS Cut Line= 6
1654669.76631576549357.3120159211654620.08498468549429.865020424
1654574.93874951549490.1706740861654506.51828267549563.171512336
  1654457.342528 549620.061818511654401.21075051549687.481959254
#Sta/Elev= 30
       0  862.24     9.3  856.94    15.1  854.02    23.1  850.95    32.5  845.78
    54.9  836.68   102.3  818.63   116.4  811.19   135.9  807.63   152.3  805.98
   173.7  805.31   187.2   805.6   191.6   804.5   196.1  801.08  198.77800.0103
   205.1   798.9   223.6   799.2  228.92800.0084   237.5  804.71   239.9  805.49
   253.8  806.79   263.6  810.04   282.6  820.57   304.9  834.04   317.7  840.53
   332.7  849.57   353.8  860.09   377.1  869.16   401.4   883.1   426.2  892.93
#Mann= 3 ,-1,0
       0      .1       0  198.77    .045       0  228.92      .1       0
Bank Sta=198.77,228.92
XS Rating Curve= 0 ,0
Exp/Cntr(USF)=0,0
Exp/Cntr=0.3,0.1

Type RM Length L Ch R = 1 ,6299    ,173.7,170.9,167.7
XS GIS Cut Line= 6
 1654429.2639562549140.7661408931654390.52157962 549219.38409388
 1654355.6873317549285.8495121451654306.38592112549372.851634726
1654269.40961712 549438.103144631654225.52212155549545.490356236
#Sta/Elev= 30
       0   875.8    10.3   874.2    35.9  867.13    49.3  865.26    90.9   851.4
   107.9  850.32   117.6  851.12   122.5  850.04   126.4  847.59   135.2  838.83
   146.8  823.46   164.9  809.64   168.7  805.99   175.8  796.13  178.01 794.654
   183.8  793.31  199.92794.6545   213.9  797.95   248.3  800.33   281.8  800.31
   303.4  801.38   310.6  802.91   323.3   807.5   334.7  808.07   359.6  820.11
   384.9  829.06   398.6  834.95   423.4  846.96   441.1  857.36   453.7  859.94
#Mann= 3 ,-1,0
       0      .1       0  178.01    .045       0  199.92      .1       0
Bank Sta=178.01,199.92
XS Rating Curve= 0 ,0
Exp/Cntr(USF)=0,0
Exp/Cntr=0.3,0.1

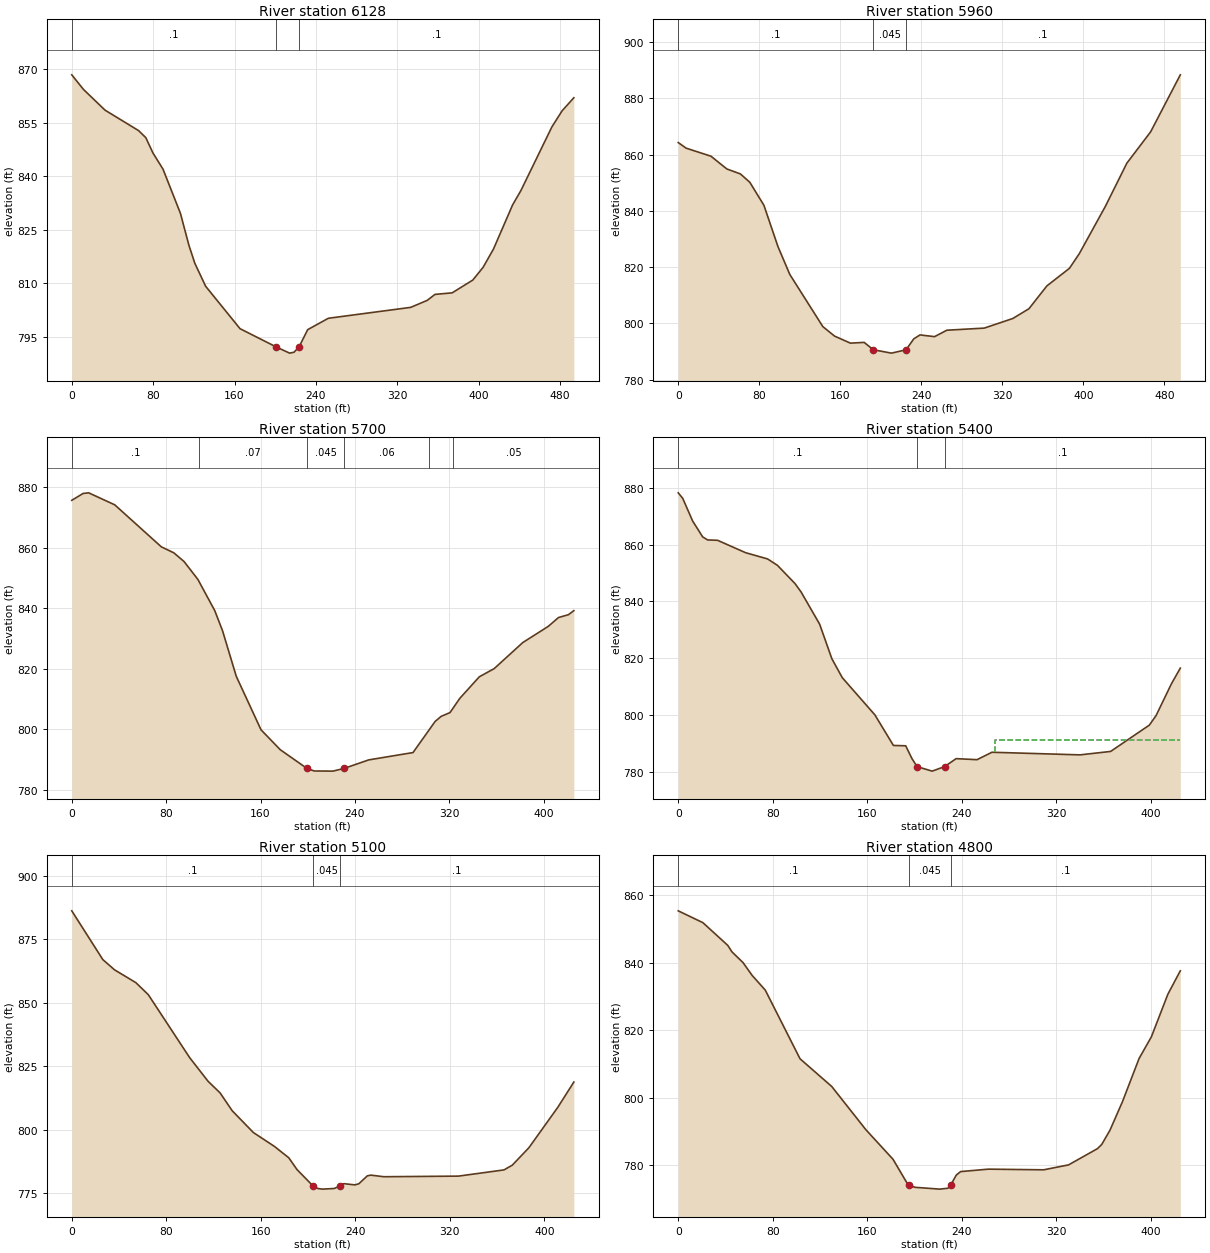
Type RM Length L Ch R = 1 ,6128    ,162.2,167.9,179.4
XS GIS Cut Line= 3
1654286.46970778549074.076165074 1654194.6435513549204.163220094
1654113.87054328549528.530615455
#Sta/Elev= 30
       0  868.49    11.5   864.4    32.7  858.59    65.7  852.85    72.8  850.87
    79.8  846.58    89.7  842.04   106.8  829.67   115.1  820.76     121  815.64
   131.6  809.22   165.4  797.33  201.03792.2051   214.1  790.48   218.4  790.72
  223.36792.2039   231.9  797.06   252.2  800.25   333.2  803.31   349.4  805.27
     357  806.94   373.9  807.38   394.2  810.96   404.3  814.53   414.5  819.65
   433.3  832.02   441.5  836.07   471.9  853.88     482  858.42   493.5  862.06
#Mann= 3 ,-1,0
       0      .1       0  201.03    .045       0  223.36      .1       0
Bank Sta=201.03,223.36
XS Rating Curve= 0 ,0
Exp/Cntr(USF)=0,0
Exp/Cntr=0.3,0.1

Type RM Length L Ch R = 1 ,5960    ,259.6,260.2,259.2
XS GIS Cut Line= 6
1654207.47622386549009.7425894951654146.99963879549075.104663498
1654089.48203728549123.5628999091654009.22366761549183.232728085
1653948.42359236549227.1456979881653822.22393679549319.826201495
#Sta/Elev= 30
       0  864.28     7.8  862.29    32.3  859.43      48  854.89    61.4  853.12
    70.7  850.15    84.6  841.98    98.5  827.27   110.2  817.36   142.8  798.82
   154.4  795.44   170.1  792.94   183.6  793.21  192.64790.5834   210.6  789.39
     225790.5825   232.6  794.47   238.8  795.87   253.1  795.25   265.3  797.54
   302.2  798.29   330.4  801.71   346.3  805.17   364.1  813.32   386.3  819.55
   396.1  824.79   421.9  841.66     443  856.94   466.5   868.1   495.8  888.37
#Mann= 3 ,-1,0
       0      .1       0  192.64    .045       0     225      .1       0
Bank Sta=192.64,225
XS Rating Curve= 0 ,0
Exp/Cntr(USF)=0,0
Exp/Cntr=0.3,0.1

Type RM Length L Ch R = 1 ,5700    ,302.5,300,296.2
XS GIS Cut Line= 6
1654054.35547309 548808.719937251653990.98781767548869.517387837
1653934.13491301548918.7042973341653854.13540109548978.704833508
1653794.37174109549024.0200315861653725.88204867549078.534030169
#Sta/Elev= 30
       0  875.63     9.6   877.9    14.3  878.11    36.4  874.15    75.9  860.25
    86.5  858.27    95.2  855.37   106.9  849.47   121.2  839.14   127.8  832.48
   139.4  817.45   160.4  799.74   176.7  793.16  199.35 786.965   205.5  786.13
   221.3  786.08  230.71786.9662   251.7   789.8   289.2  792.22   307.9  802.49
     313  804.18   320.6  805.45   328.8  810.12   345.4  817.28     358  819.98
   382.2  828.59   403.8  833.94   412.5  836.87   420.9  837.81   425.5  839.15
#Mann= 6 ,-1,0
       0      .1       0  107.82     .07       0  199.35    .045       0
  230.71     .06       0  302.99      .1       0  322.99     .05       0
Bank Sta=199.35,230.71
XS Rating Curve= 0 ,0
Exp/Cntr(USF)=0,0
Exp/Cntr=0.3,0.1

Type RM Length L Ch R = 1 ,5400    ,303.2,300.2,295.6
XS GIS Cut Line= 6
1653827.83066368548563.0786962511653772.72349042548631.045095757
1653725.48867676548689.3021970841653662.50848776548766.977894753
1653615.27367409548825.2346680021653563.07167876548895.556705832
#Sta/Elev= 30
       0   878.2     3.8  876.27    12.2  868.28    20.7  862.69    24.9  861.63
    33.3   861.5    57.1  857.13    75.6  854.95      84  852.69    98.8  846.31
     104  843.33   119.7  832.02   130.1  819.81   138.9  813.17   166.5  800.08
   182.2  789.32   192.6   789.2   197.9  784.69  202.23781.8706     215  780.29
  225.46781.8696   235.3  784.68     253  784.32   265.6  786.93   340.2  786.01
   366.1  787.22   398.9  796.48   404.6  799.85   417.6  811.03   425.1  816.53
#Mann= 3 ,-1,0
       0      .1       0  202.23    .045       0  225.46      .1       0
#XS Ineff= 2 , 0
                          268.23          791.17
Permanent Ineff=
       F       F
Bank Sta=202.23,225.46
XS Rating Curve= 0 ,0
Exp/Cntr(USF)=0,0
Exp/Cntr=0.3,0.1

Type RM Length L Ch R = 1 ,5100    ,308.2,299.8,287.6
XS GIS Cut Line= 6
1653498.75094126548400.2506098451653468.39995208548482.388568923
1653442.40328492548552.7978769241653407.49948335548646.520130426
1653381.09369625548716.6764861791653350.28699934548798.525075749
#Sta/Elev= 30
       0  886.19    26.3  866.99    36.2  862.97    54.3   857.9    64.8  853.17
    99.8  828.39   115.4  819.08   125.6  814.49   135.8  807.49   153.7  798.92
   171.6  793.43   183.7  788.97   190.7  784.31     204777.9951   208.2  776.88
   212.4  776.63   222.2  776.88  227.46 777.996   230.3  778.78   239.7   778.3
     243  778.74   250.2  781.86   253.2  782.14   264.2  781.51   327.3  781.75
   365.9   784.2   372.9  786.07   386.9  792.89   411.5  808.89     425  818.78
#Mann= 3 ,-1,0
       0      .1       0     204    .045       0  227.46      .1       0
Bank Sta=204,227.46
XS Rating Curve= 0 ,0
Exp/Cntr(USF)=0,0
Exp/Cntr=0.3,0.1

Type RM Length L Ch R = 1 ,4800    ,300.3,300,299.8
XS GIS Cut Line= 6
1653061.16848309548415.2869970951653092.70286883548496.906912595
1653119.73201425548566.8670745041653155.77196842548660.147071674
   1653182.80177548730.1069055051653213.39586893548812.090009257
#Sta/Elev= 30
       0  855.35    20.9  851.84      42  845.09    45.5  843.18    54.9  839.99
    62.5  836.24    73.7  831.85   103.1  811.51   129.9  803.32   158.9  790.47
   181.8  781.74   193.2  774.97  195.56774.1375   200.3  773.43   221.4  772.89
   228.4  773.16  230.66774.1381   235.4  777.06     239  778.08   262.5  778.81
   309.3  778.61   330.4  780.07   354.9  784.89   358.5  786.14   365.5  790.37
     376  798.77   390.1  811.59   400.5  818.01   414.5  830.66     425  837.58
#Mann= 3 ,-1,0
       0      .1       0  195.56    .045       0  230.66      .1       0
Bank Sta=195.56,230.66
XS Rating Curve= 0 ,0
Exp/Cntr(USF)=0,0
Exp/Cntr=0.3,0.1

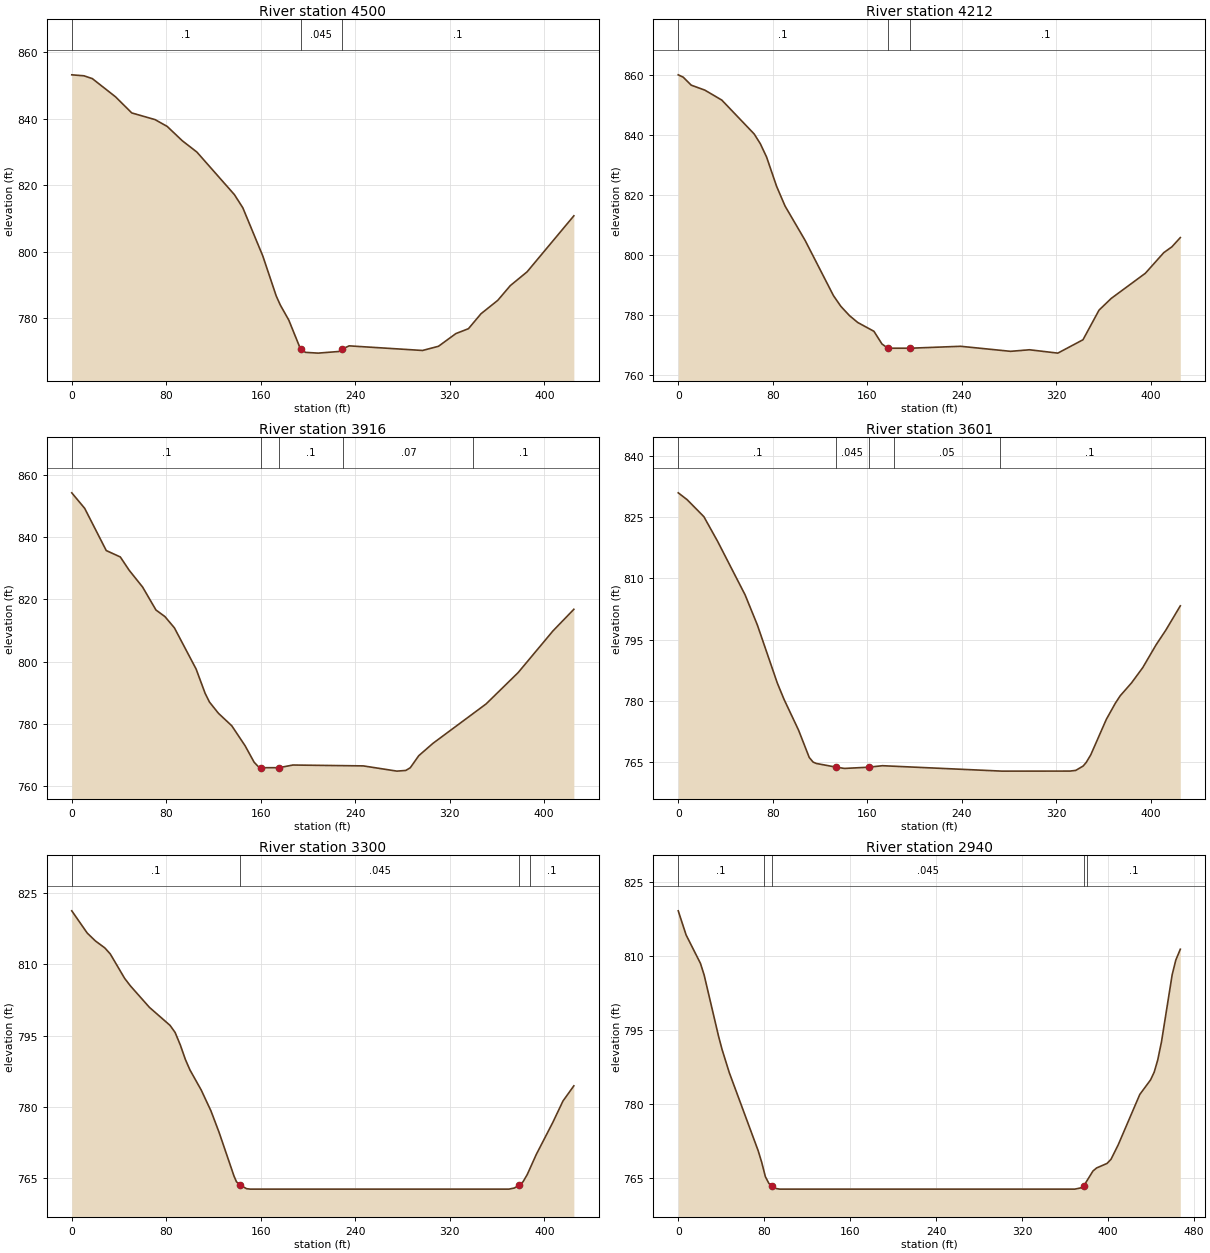
Type RM Length L Ch R = 1 ,4500    ,287.4,288.4,288.5
XS GIS Cut Line= 6
1652767.52241684548484.2366623431652800.26480542548565.379544675
1652828.32970992 548634.930914761652865.74958259548727.665637419
1652893.81415901548797.217007503 1652926.5565476548878.360217929
#Sta/Elev= 30
       0  853.24    10.3  852.95    17.4   852.1      37  846.63    50.8  841.76
    70.5  839.75    80.8  837.69    93.6  833.37   105.9  829.98   137.7  817.14
   144.8  813.19   161.7  798.68   173.1   786.6   176.6  783.85   183.7  779.37
   193.7770.5728   197.9  769.64   208.5  769.41   226.2  769.91  228.51  770.57
   234.8   771.6   296.9  770.21   310.4  771.47   325.2  775.31   335.8  776.77
   346.4  781.27   360.6  785.31   371.2  789.74   385.4  793.89     425  810.77
#Mann= 3 ,-1,0
       0      .1       0   193.7    .045       0  228.51      .1       0
Bank Sta=193.7,228.51
XS Rating Curve= 0 ,0
Exp/Cntr(USF)=0,0
Exp/Cntr=0.3,0.1

Type RM Length L Ch R = 1 ,4212    ,298.2,296,293.9
XS GIS Cut Line= 6
1652530.67310031548621.1048711131652557.19404463548704.560084778
1652579.21729456548776.2879596981652605.73298955548872.708370525
1652625.61910464548945.0241707751652650.60658747549028.900643441
#Sta/Elev= 30
       0  860.02     4.2  859.24      11  856.57    22.5  854.92    36.9  851.59
    64.3  840.29    69.5  837.04    74.8   832.6    83.3  822.81    90.4  816.28
   107.4  804.81   131.4  786.38   137.7  782.78   145.1  779.65     152   777.4
   165.7  774.46   172.5  770.23  177.44768.8195  196.47  768.82   239.1  769.46
   281.4  767.78   297.4   768.3   321.4  767.18   342.7  771.64   356.3  781.53
   366.6  785.43   395.5  793.82   411.1   800.7     418  802.65   425.1  805.72
#Mann= 3 ,-1,0
       0      .1       0  177.44    .045       0  196.47      .1       0
Bank Sta=177.44,196.47
XS Rating Curve= 0 ,0
Exp/Cntr(USF)=0,0
Exp/Cntr=0.3,0.1

Type RM Length L Ch R = 1 ,3916    ,315.2,314.5,313.5
XS GIS Cut Line= 2
1652232.60563346548773.0919503531652443.19248263549142.338587175
#Sta/Elev= 30
       0  854.18    10.9  849.22    29.2  835.64    41.1  833.58    48.6  829.31
      60   823.9    71.3  816.54    78.9  814.42    86.9  810.81   105.3  797.57
   112.9  789.79   116.6  786.97   124.2  783.36   135.5  779.35   146.8  772.92
   154.4  767.65   158.2  766.13  160.55765.8912  175.45  765.89   187.2  766.75
   246.8  766.47   275.3  764.79   282.8  765.01   286.6  765.87   293.8  769.75
   305.8  773.71   350.8  786.37   377.9  796.42   407.4  809.82   425.1  816.77
#Mann= 5 ,-1,0
       0      .1       0  160.55    .045       0  175.45      .1       0
     230     .07       0     340      .1       0
Bank Sta=160.55,175.45
XS Rating Curve= 0 ,0
Exp/Cntr(USF)=0,0
Exp/Cntr=0.3,0.1

Type RM Length L Ch R = 1 ,3601    ,297.1,301.1,362.7
XS GIS Cut Line= 6
1651959.37542251548938.0402340951652005.99672035549012.085361591
 1652045.9579265549075.5527543491652099.23931601549160.175944677
1652138.85045726549223.8638094281652184.13645593549298.749814517
#Sta/Elev= 30
       0  831.01     7.5  829.34    21.7  825.16    33.4  819.07    56.6  805.97
      67  798.57    83.8  784.39    89.5  780.37   101.9  772.75   110.9  766.07
   114.2  764.93   116.9   764.6  133.79763.6873   140.7  763.38  161.08  763.68
   172.9  764.05     274  762.72   331.6  762.73   336.5   762.9   342.8  763.98
   345.4  764.87   349.2  766.72   362.4  775.44     370  779.38   374.1   781.2
   383.7  784.37   393.2  788.12   404.5  793.72   412.6  797.25     425  803.28
#Mann= 5 ,-1,0
       0      .1       0  133.79    .045       0  161.08      .1       0
   182.5     .05       0   272.5      .1       0
Bank Sta=133.79,161.08
XS Rating Curve= 0 ,0
Exp/Cntr(USF)=0,0
Exp/Cntr=0.3,0.1

Type RM Length L Ch R = 1 ,3300    ,308.7,360.5,433.8
XS GIS Cut Line= 6
1651705.09442359549127.0608360021651763.09266718 549192.59351334
1651811.86881635549249.5658403341651876.90379126549325.529271096
1651925.68026851549382.5019261691651982.58599459549448.969969094
#Sta/Elev= 30
       0  821.24    13.1  816.56      20  814.91      28  813.44    32.6  812.17
    44.8  807.02    49.7  805.44    65.7  800.95    83.2  797.15    87.5  795.66
    91.9  793.02    96.2  789.97     100   787.8   109.6  783.55   117.8  779.18
   124.7  774.66   137.3  765.49   139.4  764.27  142.72763.5397     148  762.81
   151.2  762.72     370  762.72   374.6  762.95  378.67763.5413     382  764.27
   385.6  765.81   393.2  770.01   407.2  776.75   415.8  781.25     425  784.44
#Mann= 4 ,-1,0
       0      .1       0  142.72    .045       0  378.67    .025       0
  387.51      .1       0
Bank Sta=142.72,378.67
XS Rating Curve= 0 ,0
Exp/Cntr(USF)=0,0
Exp/Cntr=0.3,0.1

Type RM Length L Ch R = 1 ,2940    ,484.4,462.8,449.2
XS GIS Cut Line= 2
1651486.25430709549231.3811576041651580.92797041549688.906515113
#Sta/Elev= 30
       0  819.16     7.3  814.28    20.7  808.49    24.1  806.15    37.5  793.75
    40.8  791.03    47.5  786.35    74.4   770.5    77.7  768.14    81.1  765.24
    84.4  763.86   87.23763.4438    91.1  762.84    94.5  762.72     369  762.72
   375.9  763.03  377.57763.4444   385.9  766.39   389.3  767.01     399  767.93
   402.7  768.77   409.4   771.7   429.5  781.92   439.5  784.87   442.9  786.44
   446.2  788.93   449.7  792.61   459.6  806.17     463  809.17   467.2  811.37
#Mann= 5 ,-1,0
       0      .1       0      80    .025       0   87.23    .045       0
  377.57    .025       0     380      .1       0
Bank Sta=87.23,377.57
XS Rating Curve= 0 ,0
Exp/Cntr(USF)=0,0
Exp/Cntr=0.3,0.1

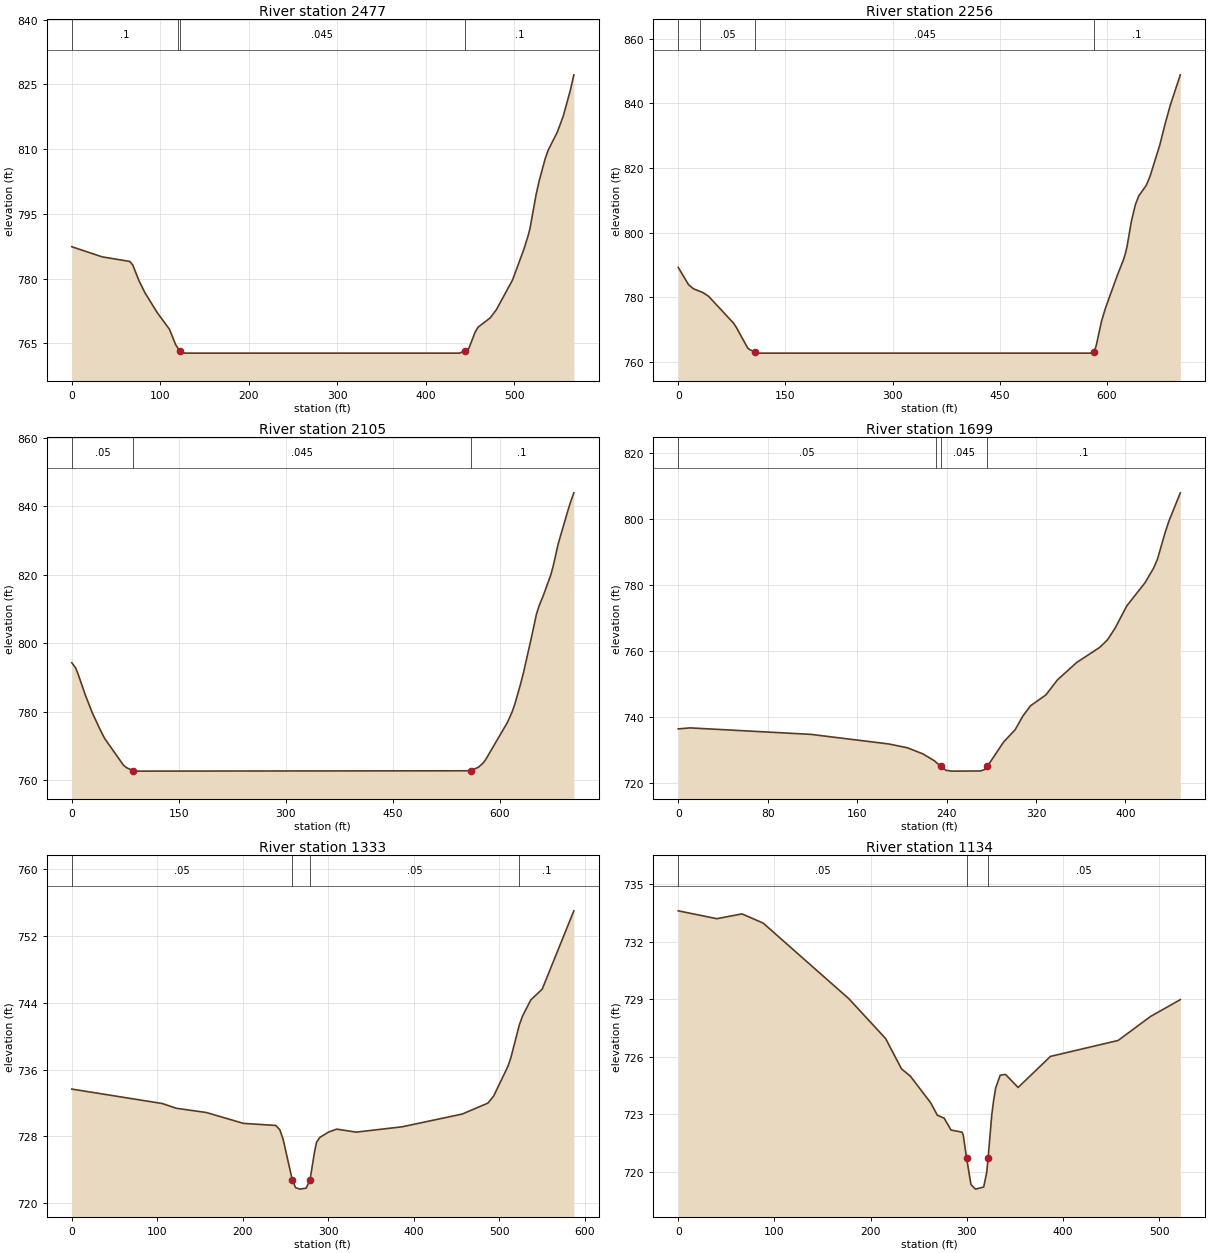
Type RM Length L Ch R = 1 ,2477    ,419,221.2,168.5
XS GIS Cut Line= 2
1650989.02619989549281.2202162821651164.69261725549820.522375584
#Sta/Elev= 30
       0  787.38    34.5  785.03    65.6  783.97      69  783.11    75.9  779.53
    82.8  776.67    96.6   772.1   110.4  768.24   117.3   764.7   121.8763.2717
   127.7  762.72   438.2  762.72  444.23763.2714   448.6  763.82   455.5   767.5
   458.9  768.72   472.7  770.89   479.7   772.8   497.9  779.66   510.7  786.75
   515.3  789.76   517.6  791.54   524.5   799.4   527.9  802.53   534.8  807.77
   538.3   809.8   548.6  813.99   555.2  817.64     563  823.46   567.2  827.23
#Mann= 4 ,-1,0
       0      .1       0     120    .025       0   121.8    .045       0
  444.23      .1       0
Bank Sta=121.8,444.23
XS Rating Curve= 0 ,0
Exp/Cntr(USF)=0,0
Exp/Cntr=0.3,0.1

Type RM Length L Ch R = 1 ,2256    ,317.7,150.9,129.9
XS GIS Cut Line= 2
1650538.68531571549436.5845430661651084.58460301 549878.81156216
#Sta/Elev= 30
       0  789.23    14.5  783.86    21.5  782.59    34.6  781.45    42.5  780.29
    77.5  771.97    81.5   770.6    97.2  764.31   100.8  763.68  108.01763.1541
   112.8  762.72   576.7  762.72  581.41763.1548   583.7  764.26   585.1  765.31
   592.3   772.6   597.5  776.46   614.6  786.92   623.1  791.67   625.7  793.54
     628  795.75     634  803.42   639.6  808.61   644.4  811.35   654.9  814.61
   660.1  817.37   673.8  827.07   681.6  833.91   688.6  839.47   702.5  848.77
#Mann= 4 ,-1,0
       0      .1       0      30     .05       0  108.01    .045       0
  581.41      .1       0
Bank Sta=108.01,581.41
XS Rating Curve= 0 ,0
Exp/Cntr(USF)=0,0
Exp/Cntr=0.3,0.1

Type RM Length L Ch R = 1 ,2105    ,539.8,405.7,413.2
XS GIS Cut Line= 2
1650348.24642768 549735.87950287   1651027.45655549919.802199844
#Sta/Elev= 30
       0  794.36     5.5  792.83     8.9  791.03    19.1  784.89    28.9  779.69
    40.2  774.63    46.3  772.19    72.3  764.51    76.9  763.71   86.26 762.822
    90.5  762.72  558.96762.8216   570.1  763.88   576.5  765.07   579.9  766.01
   610.5  776.89   617.3  780.06   620.9  782.22   628.7  787.89   632.9  791.26
   644.2  801.67   651.3  808.54   654.7   810.8   660.8  813.91   671.5  820.05
   675.1  822.87   681.9  829.17   695.4  838.79   698.9  841.15   703.7  843.95
#Mann= 3 ,-1,0
       0     .05       0   86.26    .045       0  558.96      .1       0
Bank Sta=86.26,558.96
XS Rating Curve= 0 ,0
Exp/Cntr(USF)=0,0
Exp/Cntr=0.3,0.1

Type RM Length L Ch R = 1 ,1699    ,361.9,366.2,370.5
XS GIS Cut Line= 3
1650421.73470888550207.0246225141650621.53926167550223.966879035
1650858.70020777550298.564589548
#Sta/Elev= 30
       0  736.42    10.6  736.72   118.5  734.76   188.3  731.85   205.1  730.68
   218.8  728.84   229.1  726.76  234.89725.0285   239.5  723.86   244.9  723.61
   270.4  723.66   273.8  724.05  276.45725.0284     291  732.42   301.4  736.18
   308.2  740.29   315.1  743.42   328.9  746.73   339.2  751.28   356.4  756.55
     377  761.14   383.9  763.39   390.8  766.97   401.1  773.66   417.6  780.77
   425.2  785.16   428.6  787.82   435.5  795.93   438.9  799.42   449.1     808
#Mann= 4 ,-1,0
       0     .05       0  230.52      .1       0  234.89    .045       0
  276.45      .1       0
Bank Sta=234.89,276.45
XS Rating Curve= 0 ,0
Exp/Cntr(USF)=0,0
Exp/Cntr=0.3,0.1

Type RM Length L Ch R = 1 ,1333    ,197.6,199,199.9
XS GIS Cut Line= 3
  1650286.824093550422.117668811 1650566.5514514550602.488165718
1650816.37335201550651.291295669
#Sta/Elev= 30
       0  733.68   105.8  731.95   122.3  731.38   157.5  730.87   200.8  729.57
   238.7  729.32   243.4  728.81   247.3  727.65   257.9722.8377   261.8  721.87
   266.8  721.69   274.3  721.81  278.82722.8387   283.8  726.02   286.3  727.29
   290.2  727.89   300.5  728.53   309.9  728.88   332.8  728.52   386.6  729.16
   456.9  730.69   486.9     732   493.6  732.85   510.3  736.41   513.6  737.39
   523.6  741.36   527.3  742.41     537  744.36   550.4  745.66   587.4  755.04
#Mann= 4 ,-1,0
       0     .05       0   257.9    .045       0  278.82     .05       0
  522.84      .1       0
Bank Sta=257.9,278.82
XS Rating Curve= 0 ,0
Exp/Cntr(USF)=0,0
Exp/Cntr=0.3,0.1

Type RM Length L Ch R = 1 ,1134    ,237.4,233.7,232
XS GIS Cut Line= 6
1650212.88584995550470.3952740651650286.51780438550639.421706272
1650344.63284562550686.8313883521650422.11923921550750.044188438
1650480.23362429550797.4541985971650548.03368554550852.766095845
#Sta/Elev= 30
       0   733.6    40.1  733.19    66.3  733.44    88.3  732.96   177.3  729.02
   215.6  726.94   232.1  725.36   241.3  724.98   262.3   723.6   269.4  722.94
   276.4  722.79   283.6  722.17     295  722.06   296.3   721.9  299.67720.7309
   304.3  719.33     309  719.09   317.5   719.2   320.7  719.97  322.15720.7269
   325.9  722.96   327.7  723.66     330  724.37   334.7  725.03   340.2  725.07
   353.3  724.39   386.9  726.01   457.2  726.84   490.9  728.09   521.9  728.97
#Mann= 3 ,-1,0
       0     .05       0  299.67    .045       0  322.15     .05       0
Bank Sta=299.67,322.15
XS Rating Curve= 0 ,0
Exp/Cntr(USF)=0,0
Exp/Cntr=0.3,0.1