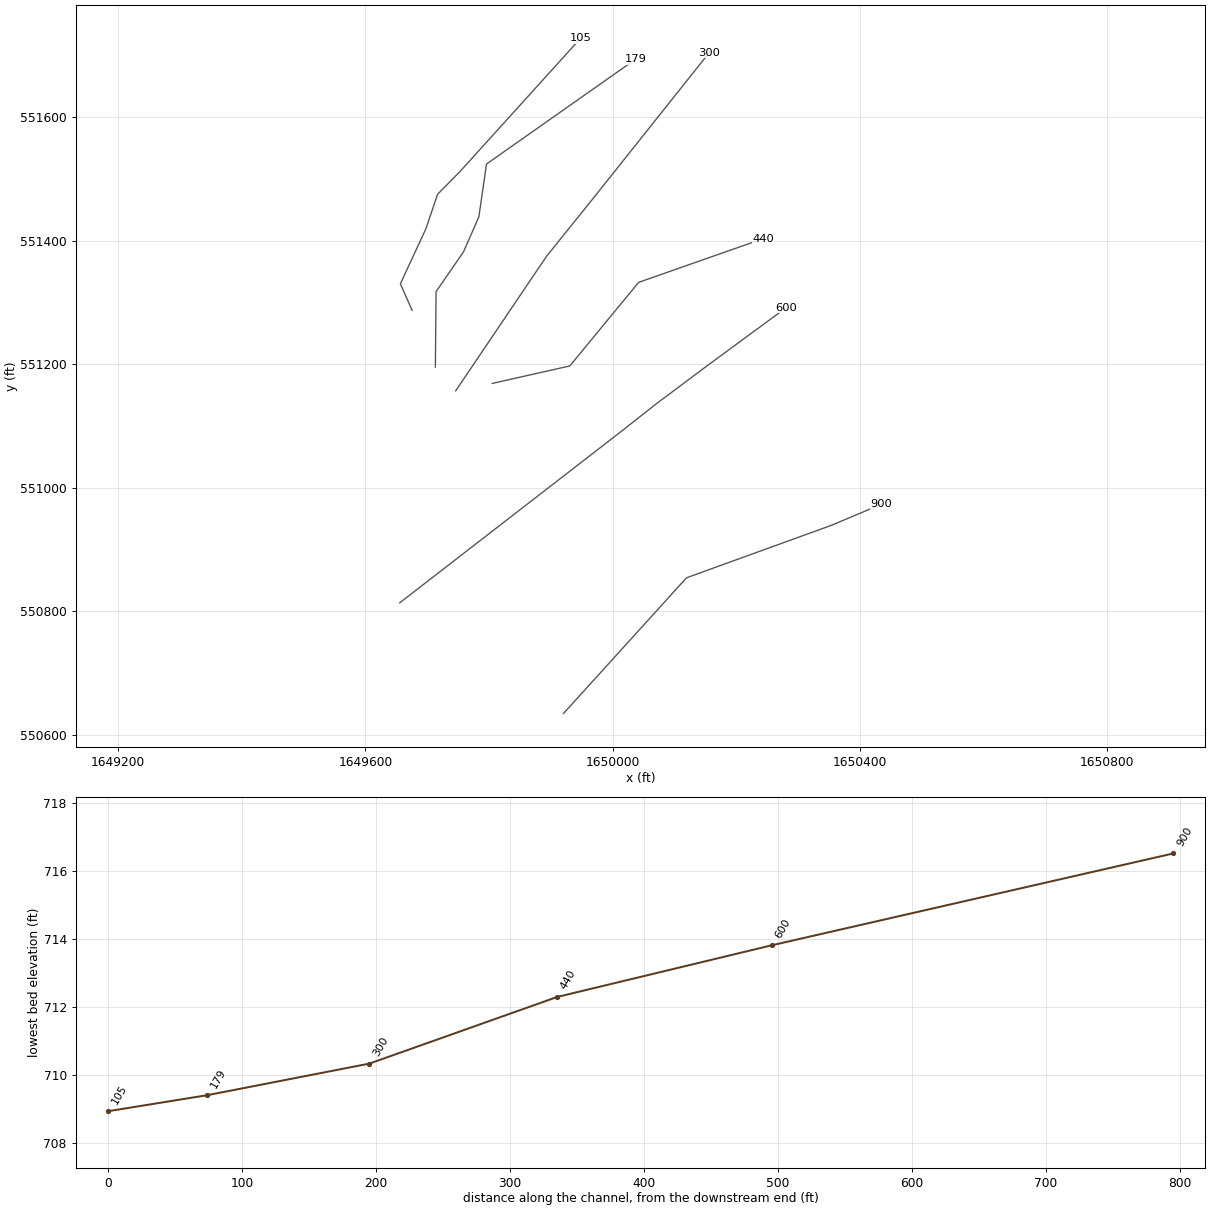
HEC-RAS study GrandstaffRn.prj: GrandstaffRn

--- GrandstaffRn.g01 (geometry) --- (continued)

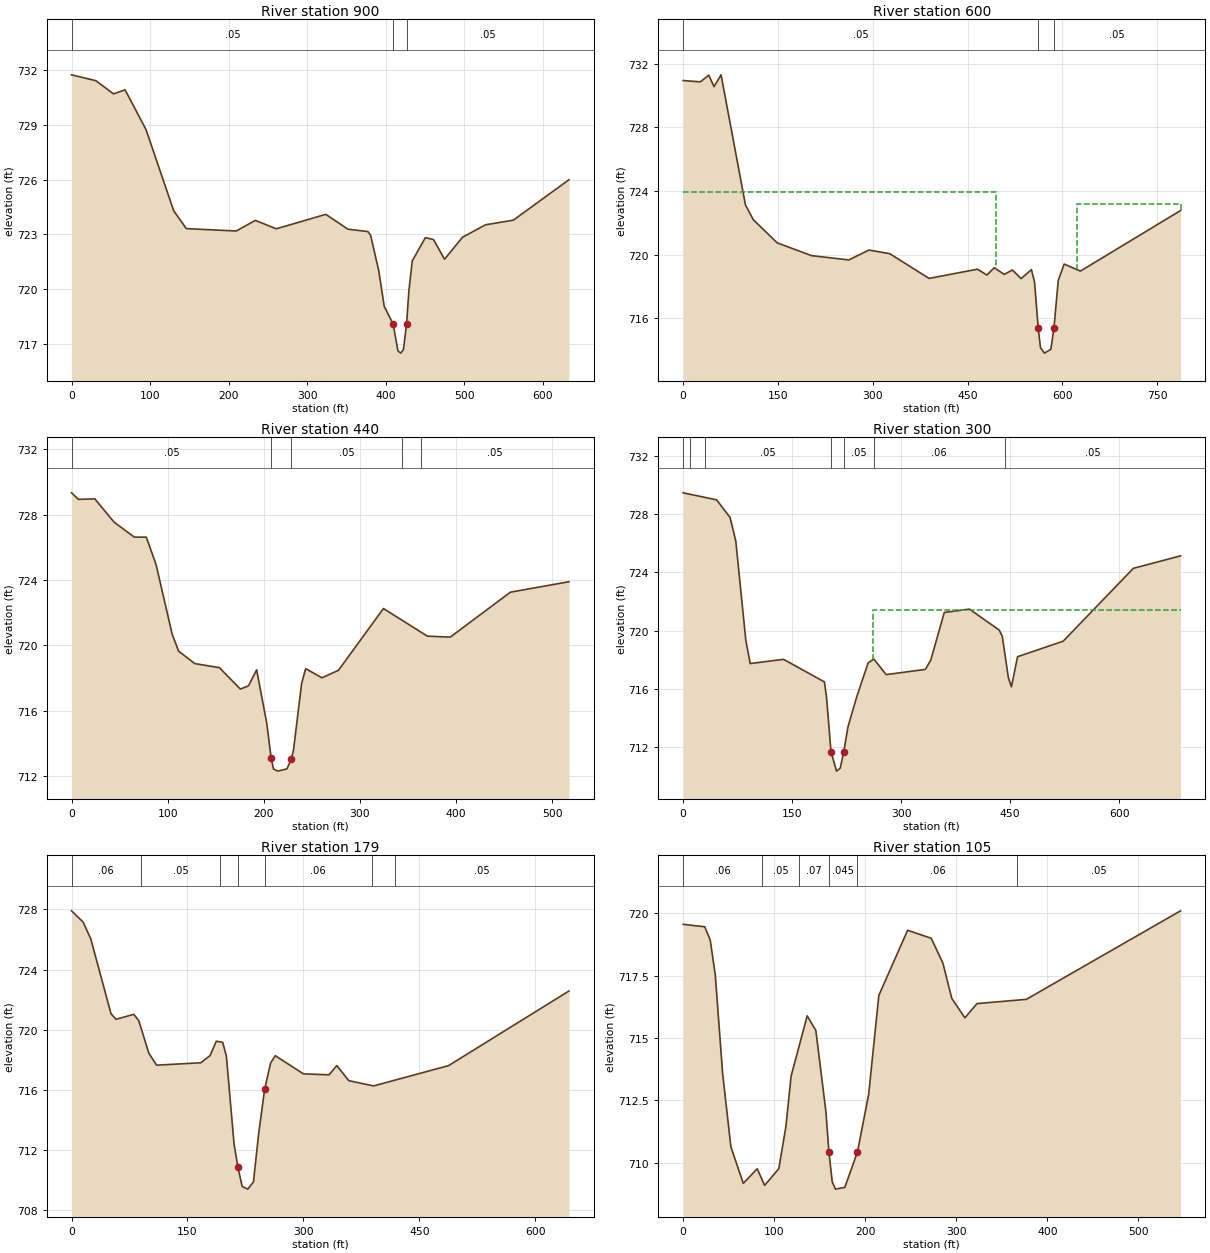
Type RM Length L Ch R = 1 ,900     ,295.8,299.6,302.6
XS GIS Cut Line= 6
 1649920.6603551550634.9000142571650119.55789651550854.233234674
1650190.07219118550879.7820680891650284.09103201550913.846960589
1650354.60532667550939.3957940041650435.33154318550973.454781011
#Sta/Elev= 30
       0  731.72      31   731.4    53.5  730.68    68.2   730.9    94.8  728.74
   130.2  724.29   146.3  723.32   209.8  723.19   234.2  723.77   260.9  723.31
   323.9   724.1   352.1  723.29   377.5  723.16     381  722.96   391.4  721.02
   398.4  719.07  409.73718.1086   415.9  716.64   419.4  716.52   422.8  716.71
  426.84718.1069   429.8  719.93   434.1  721.56   450.8  722.83   461.2  722.72
   475.2  721.65   498.1  722.85   527.5  723.53   562.8  723.78   633.7  725.99
#Mann= 3 ,-1,0
       0     .05       0  409.73    .045       0  426.84     .05       0
Bank Sta=409.73,426.84
XS Rating Curve= 0 ,0
Exp/Cntr(USF)=0,0
Exp/Cntr=0.3,0.1

Type RM Length L Ch R = 1 ,600     ,157,160.2,162.9
XS GIS Cut Line= 6
1649655.47283656 550813.778386391650010.71821918551088.592017919
1650069.66626401551135.0286048351650149.73893851551194.936949596
1650210.16270217551239.3663226661650280.65698376551291.200864673
#Sta/Elev= 30
       0  730.93    27.3  730.85    40.6  731.27    48.9  730.55      60  731.29
    98.6  723.12   111.1  722.19   148.9  720.74   203.1  719.94     262  719.67
   293.9  720.29   326.8  720.06     389  718.51   465.6  719.09   480.5  718.72
   492.1  719.18     508  718.76   520.6  719.04   534.6   718.5   550.9  719.06
   555.8  718.28  561.67715.3695   565.2  714.16   571.4  713.82   581.6  714.06
  586.42715.3684   593.3  718.39   602.7  719.41   628.4  718.97   786.7  722.77
#Mann= 3 ,-1,0
       0     .05       0  561.67    .045       0  586.42     .05       0
#XS Ineff= 2 , 0
          495.24  723.96  622.81          723.16
Permanent Ineff=
       F       F
Bank Sta=561.67,586.42
XS Rating Curve= 0 ,0
Exp/Cntr(USF)=0,0
Exp/Cntr=0.3,0.1

Type RM Length L Ch R = 1 ,440     ,138.7,140.2,141
XS GIS Cut Line= 4
1649805.21254801551168.7775590871649930.73369497551197.064014739
 1650042.1116141551332.3086308241650243.65261062551403.024769954
#Sta/Elev= 30
       0  729.33     7.2  728.93    24.2  728.96    44.2  727.54    65.3  726.62
    77.8  726.62    87.9  724.95   104.7  720.68   111.4  719.64   128.3  718.88
   153.9  718.63   175.6  717.32   184.1  717.52   192.6   718.5   203.1  715.23
   207.7  713.09   210.1  712.43   214.7   712.3   224.1  712.44   228.7  713.04
   230.9  713.58   239.4  717.67   243.6  718.57   260.6  718.01   277.7  718.47
   324.5  722.25   370.2  720.56     394   720.5   456.6  723.25   517.5  723.89
#Mann= 5 ,-1,0
       0     .05       0   207.7    .045       0   228.7     .05       0
  343.87     .06       0  363.87     .05       0
Bank Sta=207.7,228.7
XS Rating Curve= 0 ,0
Exp/Cntr(USF)=0,0
Exp/Cntr=0.3,0.1

Type RM Length L Ch R = 1 ,300     ,118.6,121.2,126.7
XS GIS Cut Line= 6
1649746.06947026551156.8139943331649795.04410984551229.324019924
1649837.02237234551291.4757985031649892.99306092551374.345055342
 1649968.1544537551467.7300680581650156.40979225551704.084748751
#Sta/Elev= 30
       0  729.46      46  728.98    64.6  727.77    72.5  726.14    86.2  719.36
    92.3  717.73   138.2  718.02   194.4  716.47   197.3  715.44  203.49 711.674
   211.1  710.34   216.2  710.54  221.03711.6755   226.9  713.39   238.8  715.43
   254.6  717.78   262.5  718.04   279.4  716.97   333.4  717.33   340.8  717.97
   359.4  721.24   394.1  721.47     435  720.03   439.2   719.6   447.6  716.75
   451.8  716.13   460.2   718.2   523.1  719.27   619.5  724.27   684.5  725.13
#Mann= 7 ,-1,0
       0     .05       0      10     .06       0      30     .05       0
  203.49    .045       0  221.03     .05       0   262.5     .06       0
  442.38     .05       0
#XS Ineff= 2 , 0
                          261.16           721.4
Permanent Ineff=
       F       F
Bank Sta=203.49,221.03
XS Rating Curve= 0 ,0
Exp/Cntr(USF)=0,0
Exp/Cntr=0.3,0.1

Type RM Length L Ch R = 1 ,179     ,72.7,73.9,75.1
XS GIS Cut Line= 6
1649713.19035805551195.3650614441649714.31999195551317.365522515
1649758.63522723551381.4891153281649783.57353888551438.325267459
1649795.90043009551523.7705064771650037.53314477551693.576061403
#Sta/Elev= 30
       0  727.91      15  727.16    24.8  726.06    51.1  721.07    57.6   720.7
    80.6  721.03      87  720.61     100  718.45   110.1  717.65   167.4  717.81
   179.3  718.29   187.3  719.24   195.6  719.17   200.4  718.25   210.3  712.42
   215.4710.8478   220.8  709.59     228  709.41   235.4  709.89   242.3  713.16
   249.9716.0414   257.6  717.79   263.7  718.28   300.2  717.07   333.3  717.01
   343.3  717.62   358.8  716.62   390.9  716.27   487.9  717.62   643.7  722.58
#Mann= 7 ,-1,0
       0     .06       0      90     .05       0  192.01     .06       0
   215.4    .045       0   249.9     .06       0  388.35      .1       0
  418.35     .05       0
Bank Sta=215.4,249.9
XS Rating Curve= 0 ,0
Exp/Cntr(USF)=0,0
Exp/Cntr=0.3,0.1

Type RM Length L Ch R = 1 ,105     ,,,
XS GIS Cut Line= 6
1649675.57015258551287.0100602481649656.57427448551329.985934307
1649697.94141563551419.2224877341649716.62903935551474.640958066
1649753.93268669551512.660606318 1649948.1012524551727.165257681
#Sta/Elev= 30
       0  719.56    23.8  719.46    29.8  718.92    35.3  717.54    43.4  713.57
    52.5  710.63    66.1  709.17    81.4  709.76    89.5  709.09   105.1  709.76
   112.9  711.45   118.6  713.47   136.3  715.89   145.8   715.3   156.9  712.03
160.1538710.4203   163.8  709.23   167.3  708.94   177.6  709.01191.5038710.4307
   203.8  712.74     215  716.71   246.6  719.32   272.5     719   285.3  718.01
   295.1  716.59   309.5  715.81   322.8  716.38     377  716.55   546.4   720.1
#Mann= 6 ,-1,0
       0     .06       0   86.99     .05       0  126.99     .07       0
160.1538    .045       0191.5038     .06       0  367.09     .05       0
Bank Sta=160.1538,191.5038
XS Rating Curve= 0 ,0
Exp/Cntr(USF)=0,0
Exp/Cntr=0.3,0.1
LCMann Table=0

Chan Stop Cuts=-1
Use User Specified Reach Order=0
Composite Channel Slope=5